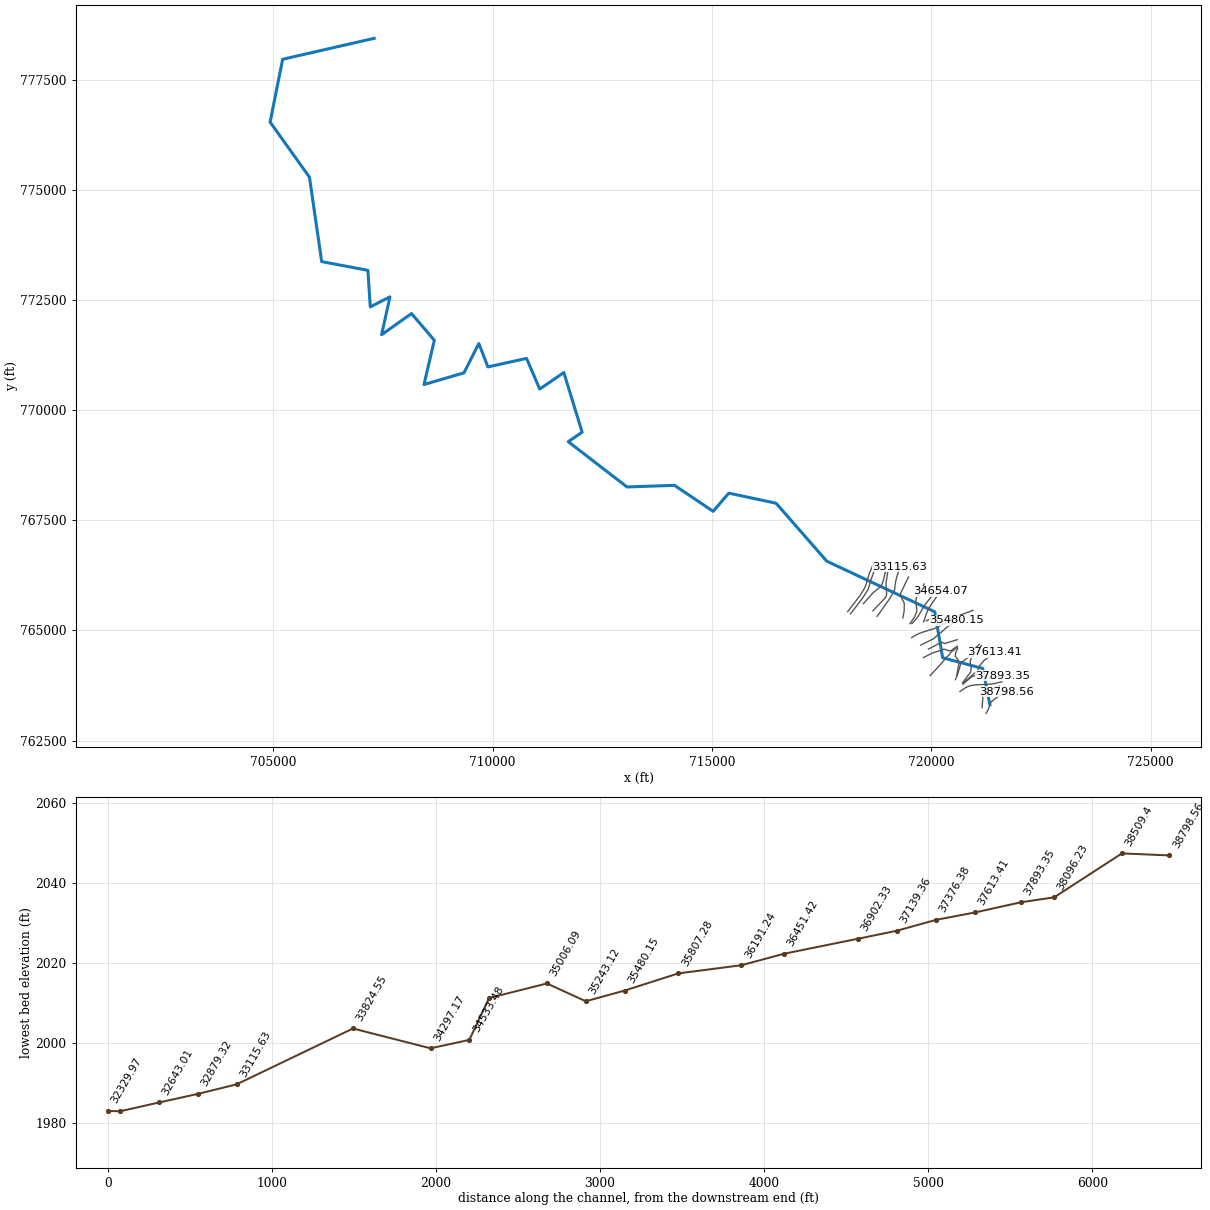
--- 14492_ras.prj (project) ---

Proj Title=14492
Current Plan=p01
Default Exp/Contr=0.3,0.1
English Units
Geom File=g01
Flow File=f01
Plan File=p01
Y Axis Title=Elevation
X Axis Title(PF)=Main Channel Distance
X Axis Title(XS)=Station
BEGIN DESCRIPTION:
RFD model 14492 exported to HEC-RAS
END DESCRIPTION:

--- 14492_ras.p01 (plan) ---

Plan Title=Plan 01
Program Version=4.10
Short Identifier=Plan 01
Geom File=g01
Flow File=f01
Subcritical Flow
Calc Critical at every XS
Secant Critical Depth

--- 14492_ras.f01 (steady flow) ---

Flow Title=Flow 01
Program Version=5.01
Number of Profiles= 6
Profile Names=10yr,25yr,50yr,100yr,100plus,500yr
River Rch & RM=14492,111,38798.56
  248.92  409.55  563.23  708.15  1033.9 1749.07
River Rch & RM=14492,111, 38509.4
  393.45  649.54  895.61 1127.95 1646.81 2617.04
River Rch & RM=14492,111,38096.23
  529.59  877.95 1214.19 1532.66 2237.68 3421.51
River Rch & RM=14492,111,37893.35
  532.51  882.87 1221.07 1541.41 2250.46 3438.64
River Rch & RM=14492,111,37613.41
  540.72  896.69  1240.4 1566.03 2286.41 3486.74
River Rch & RM=14492,111,37376.38
  544.12  902.45 1248.46  1576.3  2301.4 3506.83
River Rch & RM=14492,111,37139.36
  548.57  909.95 1258.98 1589.71 2320.97 3533.03
River Rch & RM=14492,111,36902.33
  549.35  911.28 1260.83 1592.07 2324.42 3537.65
River Rch & RM=14492,111,36451.42
  556.14  922.73 1276.87 1612.53 2354.29 3577.56
River Rch & RM=14492,111,36191.24
  560.05  929.33 1286.11  1624.3 2371.48 3600.51
River Rch & RM=14492,111,35807.28
  560.83  930.65 1287.96 1626.66 2374.92 3605.09
River Rch & RM=14492,111,35480.15
  568.36  943.37 1305.78 1649.37 2408.08 3649.27
River Rch & RM=14492,111,35243.12
  574.06  952.99 1319.26 1666.56 2433.18 3682.65
River Rch & RM=14492,111,35006.09
  576.11  956.46 1324.12 1672.77 2442.25 3694.76
River Rch & RM=14492,111,34654.07
  673.37 1121.46 1555.95  1969.1 2874.89 4266.25
River Rch & RM=14492,111,34533.48
  675.07 1124.35 1560.02 1974.32 2882.51 4276.25
River Rch & RM=14492,111,34297.17
  676.53 1126.83 1563.51  1978.8 2889.04 4284.82
River Rch & RM=14492,111,33824.55
  738.49 1232.79 1713.18 2170.98 3169.63 4652.58
River Rch & RM=14492,111,33115.63
  752.94  1257.3 1747.62    2215  3233.9 4735.19
River Rch & RM=14492,111,32879.32
  792.41 1324.35 1841.93 2335.65 3410.05 4960.85
River Rch & RM=14492,111,32643.01
  794.04 1327.13 1845.85 2340.68 3417.39 4970.28
River Rch & RM=14492,111,32406.71
   796.6  1331.5 1852.02 2348.58 3428.93 4985.08
River Rch & RM=14492,111,31939.71
  838.11 1402.48  1952.3 2477.36 3616.94 5226.18
River Rch & RM=14492,111,31549.44
  846.98 1417.66 1973.75 2504.91 3657.17 5277.56
River Rch & RM=14492,111,31159.17
  849.94 1422.72  1980.9 2514.09 3670.57 5294.64
River Rch & RM=14492,111, 31066.5
  872.38 1461.32 2035.63 2584.59  3773.5 5426.62
River Rch & RM=14492,111,30693.04
  899.07 1507.03 2100.27 2667.65 3894.77 5580.53
River Rch & RM=14492,111,30319.57
  990.28 1663.93 2322.78 2954.33 4313.32 6109.81
River Rch & RM=14492,111,29924.13
  998.23  1677.6 2342.19 2979.34 4349.84 6155.67
River Rch & RM=14492,111,29528.68
  1018.1 1711.83 2390.77 3041.98 4441.29 6270.36
River Rch & RM=14492,111,29085.53
 1034.61 1740.31 2431.24 3094.19 4517.52 6365.92
River Rch & RM=14492,111,28703.86
 1058.61 1781.72  2490.1 3170.16 4628.43 6504.57
River Rch & RM=14492,111,28322.19
 1070.55 1802.34  2519.4 3207.99 4683.66 6573.47
River Rch & RM=14492,111, 27895.9
  1073.9 1808.11 2527.61 3218.58 4699.13 6592.76
River Rch & RM=14492,111, 27469.6
 1391.79 2349.35 3290.47 4195.58 6125.54 8300.35
River Rch & RM=14492,111, 27043.3
 1421.56 2400.89  3363.9 4290.52 6264.16 8466.98
River Rch & RM=14492,111,26617.01
 1474.72  2493.2 3495.66 4461.15 6513.28 8766.31
River Rch & RM=14492,111,26531.99
 1475.88 2495.21 3498.52 4464.85 6518.69 8772.78
River Rch & RM=14492,111,26315.67
 1489.58 2518.94 3532.36 4508.64 6582.61 8849.11
River Rch & RM=14492,111,26099.35
 1496.52 2530.98 3549.52 4530.82    6615 8887.71
River Rch & RM=14492,111,25883.03
 1497.87 2533.31 3552.84 4535.12 6621.28 8895.21
River Rch & RM=14492,111,25806.06
 1504.18 2544.26 3568.48 4555.37 6650.84 8930.53
River Rch & RM=14492,111,25319.14
 1813.72  3076.9 4324.56  5529.5 8073.0710583.58
River Rch & RM=14492,111,25075.68
 1816.84 3082.32 4332.29 5539.52 8087.7110600.58
River Rch & RM=14492,111,24832.22
 1819.96 3087.73 4340.03 5549.54 8102.3310617.57
River Rch & RM=14492,111, 24345.3
 1866.14 3167.99 4454.69  5698.1 8319.2310869.18
River Rch & RM=14492,111,24101.84
 1869.42 3173.69 4462.83 5708.65 8334.62   10887
River Rch & RM=14492,111,23858.38
  1872.7 3179.39 4470.96 5719.19 8350.01 10904.8
River Rch & RM=14492,111,23235.48
 1936.74    3291 4630.72 5926.51  8652.711255.57
River Rch & RM=14492,111,22641.08
 1874.88 3183.18 4476.38 5726.21 8360.2610916.66
River Rch & RM=14492,111,22154.17
  1941.2 3298.77 4641.84 5940.95 8673.7911279.97
River Rch & RM=14492,111,21667.25
 1944.21 3304.04 4649.39 5950.76  8688.111296.56
River Rch & RM=14492,111,20927.75
 1950.42 3314.88 4664.92 5970.93 8717.5611330.66
River Rch & RM=14492,111,20380.57
 1967.12  3344.1 4706.85 6025.47 8797.1911423.04
River Rch & RM=14492,111,19963.03
 1970.48 3349.96 4715.26 6036.39 8813.1311441.48
River Rch & RM=14492,111,19309.22
 1974.37 3356.76 4724.99 6049.04 8831.5911462.82
River Rch & RM=14492,111,18916.49
 1977.19  3361.7 4732.07 6058.23 8845.0211478.33
River Rch & RM=14492,111,18237.72
 2032.95 3459.62 4872.91 6241.78    911311789.67
River Rch & RM=14492,111,17440.89
 3515.79 5997.74 8465.4810854.8815848.1318993.74
River Rch & RM=14492,111,16949.03
  3602.2 6150.35 8685.8711142.9116268.6519446.43
River Rch & RM=14492,111,16088.68
 3614.96 6172.75  8718.1 11184.916329.9619511.77
River Rch & RM=14492,111,15473.43
 3622.27 6185.54 8736.4611208.7816364.8219548.73
River Rch & RM=14492,111, 15227.5
 3626.17 6192.36 8746.25 11221.516383.3919568.38
River Rch & RM=14492,111,14981.57
 3628.99 6197.28 8753.3111230.6716396.7819582.53
River Rch & RM=14492,111, 14489.7
 3670.47 6269.55 8856.7911364.8916592.7419788.72
River Rch & RM=14492,111,13997.84
 3674.23 6276.11 8866.1911377.0916610.5519807.49
River Rch & RM=14492,111,13751.91
 3676.25 6279.64 8871.2611383.6716620.1619817.66
River Rch & RM=14492,111,13307.04
 3706.98 6333.31 8948.2211483.63 16766.119971.47
River Rch & RM=14492,111,13031.78
 3709.74 6338.14 8955.1811492.6916779.33 19985.5
River Rch & RM=14492,111,12318.45
 3720.56 6357.16 8982.5611528.3716831.42 20040.8
River Rch & RM=14492,111,11693.67
 3726.24 6367.11 8996.8611546.9916858.61 20069.6
River Rch & RM=14492,111,10308.85
 3769.26 6442.56 9105.3611688.2517064.8420287.77
River Rch & RM=14492,111,9721.021
 3775.84  6454.1 9121.9511709.8417096.3720321.08
River Rch & RM=14492,111,9325.122
 3780.39  6462.1 9133.4611724.8517118.28 20344.3
River Rch & RM=14492,111,9079.189
 3783.53 6467.64 9141.4611735.3117133.5520360.55
River Rch & RM=14492,111,8833.257
 3785.48 6471.07 9146.4211741.7717142.9920370.61
River Rch & RM=14492,111,8587.325
 3792.21 6482.95 9163.5611764.1717175.6820405.41
River Rch & RM=14492,111,8341.392
 3794.46 6486.91 9169.2711771.6317186.58   20417
River Rch & RM=14492,111, 8095.46
 4128.64 7068.3710001.3112850.0318761.0422050.28
River Rch & RM=14492,111,7849.527
 4132.33 7074.8810010.6812862.2718778.9122069.02
River Rch & RM=14492,111,7504.228
 4136.75 7082.6710021.9312876.9418800.3422091.51
River Rch & RM=14492,111, 7111.73
 4162.93 7128.8210088.52 12963.918927.2922224.72
River Rch & RM=14492,111,6865.797
 4165.09 7132.6510094.0712971.17 18937.922235.93
River Rch & RM=14492,111,6619.865
 4170.22 7141.77 10107.312988.5318963.2522262.83
River Rch & RM=14492,111,    6128
 4173.07 7146.8410114.6512998.1718977.3322277.77
River Rch & RM=14492,111,5882.068
 4176.06 7152.1610122.37 13008.318992.1222293.45
River Rch & RM=14492,111,5827.237
 4176.34 7152.6710123.1113009.2618993.5322294.94
River Rch & RM=14492,111,5401.752
 4285.88 7348.1710407.3613382.9219539.0722875.09
River Rch & RM=14492,111,5189.008
  4288.7  7353.210414.6613392.5119553.0622889.87
River Rch & RM=14492,111,4763.523
 4292.19 7359.4310423.7113404.4219570.4522908.34
River Rch & RM=14492,111, 4550.78
 4294.52 7363.6210429.8213412.4719582.2122920.89
River Rch & RM=14492,111,4304.381
  4294.8 7364.1110430.5413413.4219583.5922922.37
River Rch & RM=14492,111,3968.811
 4303.03 7378.8910452.0913441.8319625.0722966.66
River Rch & RM=14492,111,3700.986
 4308.23 7388.2210465.7213459.79 19651.3 22994.7
Boundary for River Rch & Prof#=14492,111,1
Up Type= 0
Dn Type= 2
Boundary for River Rch & Prof#=14492,111,2
Up Type= 0
Dn Type= 2
Boundary for River Rch & Prof#=14492,111,2
Up Type= 0
Dn Type= 2
Boundary for River Rch & Prof#=14492,111,2
Up Type= 0
Dn Type= 2
Boundary for River Rch & Prof#=14492,111,2
Up Type= 0
Dn Type= 2
Boundary for River Rch & Prof#=14492,111,2
Up Type= 0
Dn Type= 2

--- 14492_ras.g01 (geometry) ---

Geom Title=14492
Program Version=4.10

River Reach=14492,111
Reach XY= 30
 721337.24620977763315.471495673721172.662876427764138.040940166
720259.815654218 764380.26316236720077.662876457765424.290940151
717616.461753041766572.832944661716461.760098696767886.860384583
715383.843431979 768116.02705127715026.760098666767703.527051255
714144.260098696768293.110384598713062.514126658768256.208757848
711722.280931979769283.631217912712039.503154218769499.186773479
711622.280931979770852.520106807711072.280932009770477.520106807
710771.725376427771173.075662374  709891.4278934770980.105306998
709683.962341368771511.355455488709345.420936465770845.556728035
708433.094407767770579.931648836708669.429870218771583.865083143
708149.642043114772191.131217927707467.811415315771711.209691092
707657.928217381 772570.84401983707209.143268883772341.677444279
707154.455845058  773171.5386976706100.636628777773369.455382302
705822.853848696775284.030523494704925.553265333776534.686268449
705211.178883702777960.494055018707296.266554505778435.499842674

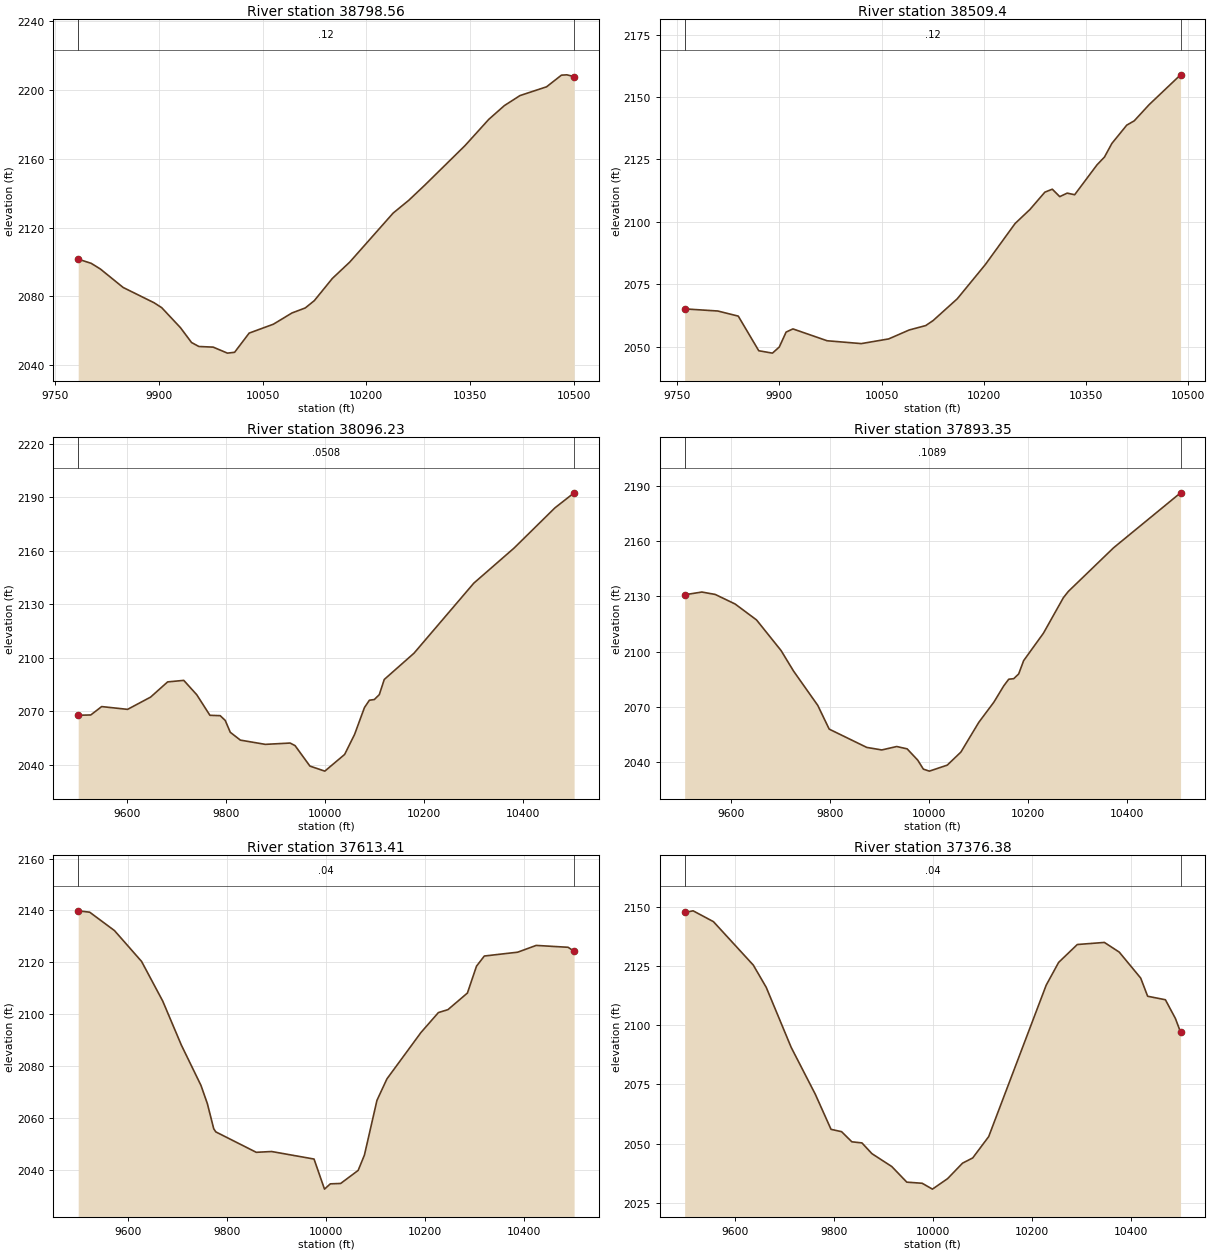
Type RM Length L Ch R = 1 ,38798.56,289.155000,289.155000,289.155000
XS GIS Cut Line= 6
721248.798109149763118.776998669721299.035348381763208.728466616
721345.677669404763345.703788622721367.423298594763380.680854472
721509.956265016763494.281754961721724.302332707 763613.54820534
#Sta/Elev= 30
9783.347  2101.69802.1442099.1499815.4272095.8439848.3212085.1089893.2612076.166
9904.1952073.3229931.2582061.6999947.3912053.0219957.9722050.7299978.6262050.361
9999.2542046.86910009.612047.35210030.692058.52410065.732063.70710092.672070.256
10111.822073.16610124.912077.39710151.082090.35110176.162099.84110239.012128.403
10261.372135.76110284.732144.63510343.122167.738 10377.42182.97210399.992190.998
10422.592196.82610461.012201.926 10482.52208.70610490.372208.90110500.882207.859
#Mann= 3 , 0 , 0
9783.347    0.12       09783.347    0.12       010500.88    0.12       0
#XS Ineff= 2 , 0
       0                               0
Bank Sta=9783.347,10500.88
Exp/Cntr=0.3,0.1

Type RM Length L Ch R = 1 , 38509.4,413.176100,413.176100,413.176100
XS GIS Cut Line= 4
721158.568726182763246.530679703721171.869091362763423.868881524
721185.169456452763577.561989754721547.234951854 763737.16637139
#Sta/Elev= 30
9761.0482065.1059809.6542064.2519839.7382062.2069869.822 2048.339889.8792047.374
9899.9072049.8179909.9352055.8049919.9632057.0799970.1322052.33210020.322051.192
10060.47 2053.0710090.582056.64610114.822058.41610125.752060.43810161.182069.168
10202.252082.84210245.972099.31110267.822104.95510289.682111.88410300.612113.066
10311.542110.08810322.472111.49710333.392110.84710366.182122.81510377.112125.932
10388.042131.41310409.892138.75310420.822140.45810442.682146.94210488.842158.905
#Mann= 3 , 0 , 0
9761.048    0.12       09761.048    0.12       010488.84    0.12       0
#XS Ineff= 2 , 0
       09924.587                       0
Bank Sta=9761.048,10488.84
Exp/Cntr=0.3,0.1

Type RM Length L Ch R = 1 ,38096.23,202.880000,202.880000,202.880000
XS GIS Cut Line= 6
720654.908786262763616.032798624720786.350833143763706.034415117
720902.195685701763750.799933154721024.797725688763767.421895042
721369.836933581763782.259860104721612.474425381763834.135524325
#Sta/Elev= 30
9501.9942067.7549527.3822067.9179549.3762072.6199601.7162071.0589648.3022077.955
9682.6142086.4749715.2682087.331 9741.562079.2419768.0772067.7169788.8572067.521
9799.0342064.8339809.2112058.1839829.5652053.7989879.9222051.4099930.0872052.147
9940.1022050.7029970.1462039.20710000.182036.38710040.232045.75710060.242056.927
10080.24 2072.0610090.252076.18710100.25 2076.5810110.262079.33210120.262087.839
10180.322102.57110301.122141.88810382.522161.59710464.97 2184.1510503.842192.609
#Mann= 3 , 0 , 0
9501.994  0.0508       09501.994  0.0508       010503.84  0.0508       0
#XS Ineff= 2 , 0
       0                               0
Bank Sta=9501.994,10503.84
Exp/Cntr=0.3,0.1

Type RM Length L Ch R = 1 ,37893.35,279.935100,279.935100,279.935100
XS GIS Cut Line= 6
720719.166234084763777.791483948720910.912326497763941.211585168
721019.845199454763991.396350479721081.207121754 763990.91953115
721304.069826242763916.334573117 721625.70797455763972.568957014
#Sta/Elev= 30
9507.0562130.8359541.836 2132.329568.7622131.0259609.1512125.8029652.243 2117.18
9701.732  2100.69726.9662089.448 9775.95  2070.89798.9622057.9479874.7772048.024
9905.1072046.6419935.3422048.5039956.3682047.2319977.7812041.1159989.2092036.217
10001.272035.15110037.382038.40510064.952045.49110101.062061.60910131.462072.536
10151.532081.42510161.572085.01910171.612085.31410181.642087.88410191.642095.094
10231.662110.00410271.81 2129.2110281.872132.63710373.372156.35310508.57 2186.15
#Mann= 3 , 0 , 0
9507.056  0.1089       09507.056  0.1089       010508.57  0.1089       0
#XS Ineff= 2 , 0
       0                               0
Bank Sta=9507.056,10508.57
Exp/Cntr=0.3,0.1

Type RM Length L Ch R = 1 ,37613.41,237.029200,237.029200,237.029200
XS GIS Cut Line= 6
720731.572006291763809.131305442721036.617276016764074.195357817
 721063.85317664764111.723510055721107.391206145764208.673320246
721198.054187255 764314.14373867721437.921639052764501.972548605
#Sta/Elev= 30
9499.086 2139.87 9522.282139.3439572.3432132.2559627.0482120.377  9669.72105.135
9707.541 2088.089747.0382072.5989759.9742065.5639772.9092055.8459777.1462054.653
9858.7732046.7929889.8082047.0989975.4592044.1979996.5952032.60210008.342034.633
10029.282034.79110064.612039.81610077.262045.73410102.562066.80610122.662075.075
10191.392092.955 10226.72100.65610245.982101.78610285.282108.17510303.632118.528
10319.442122.44810386.89 2123.9310424.232126.53910488.652125.81610500.862124.279
#Mann= 3 , 0 , 0
9499.086    0.04       09499.086    0.04       010500.86    0.04       0
#XS Ineff= 2 , 0
       0                               0
Bank Sta=9499.086,10500.86
Exp/Cntr=0.3,0.1

Type RM Length L Ch R = 1 ,37376.38,237.029300,237.029300,237.029300
XS GIS Cut Line= 6
 720712.38337941 763812.44032238720895.563196119764052.744375026
720911.165884632764154.143578867720884.966365108 764292.15179395
720913.384971496764378.930325613721142.413183325764656.483345108
#Sta/Elev= 30
 9499.152147.7619516.3062148.4389557.2842143.8649637.8832125.4719663.9552116.061
9714.4432090.6429763.1822070.8189794.7742056.0449816.1522055.0449836.798 2050.77
9857.2172050.2999877.3572045.7619917.4692040.3159947.8242033.7089978.8732033.232
9999.6192030.75510030.25 2035.1910060.422041.74210080.942043.93510113.222052.957
10229.39 2117.0110254.512126.632 10292.22134.19210346.932135.07510376.962130.974
10420.252120.00110434.282112.31810470.12 2110.8410490.372102.90710500.762097.136
#Mann= 3 , 0 , 0
 9499.15    0.04       0 9499.15    0.04       010500.76    0.04       0
#XS Ineff= 2 , 0
       0                               0
Bank Sta=9499.15,10500.76
Exp/Cntr=0.3,0.1

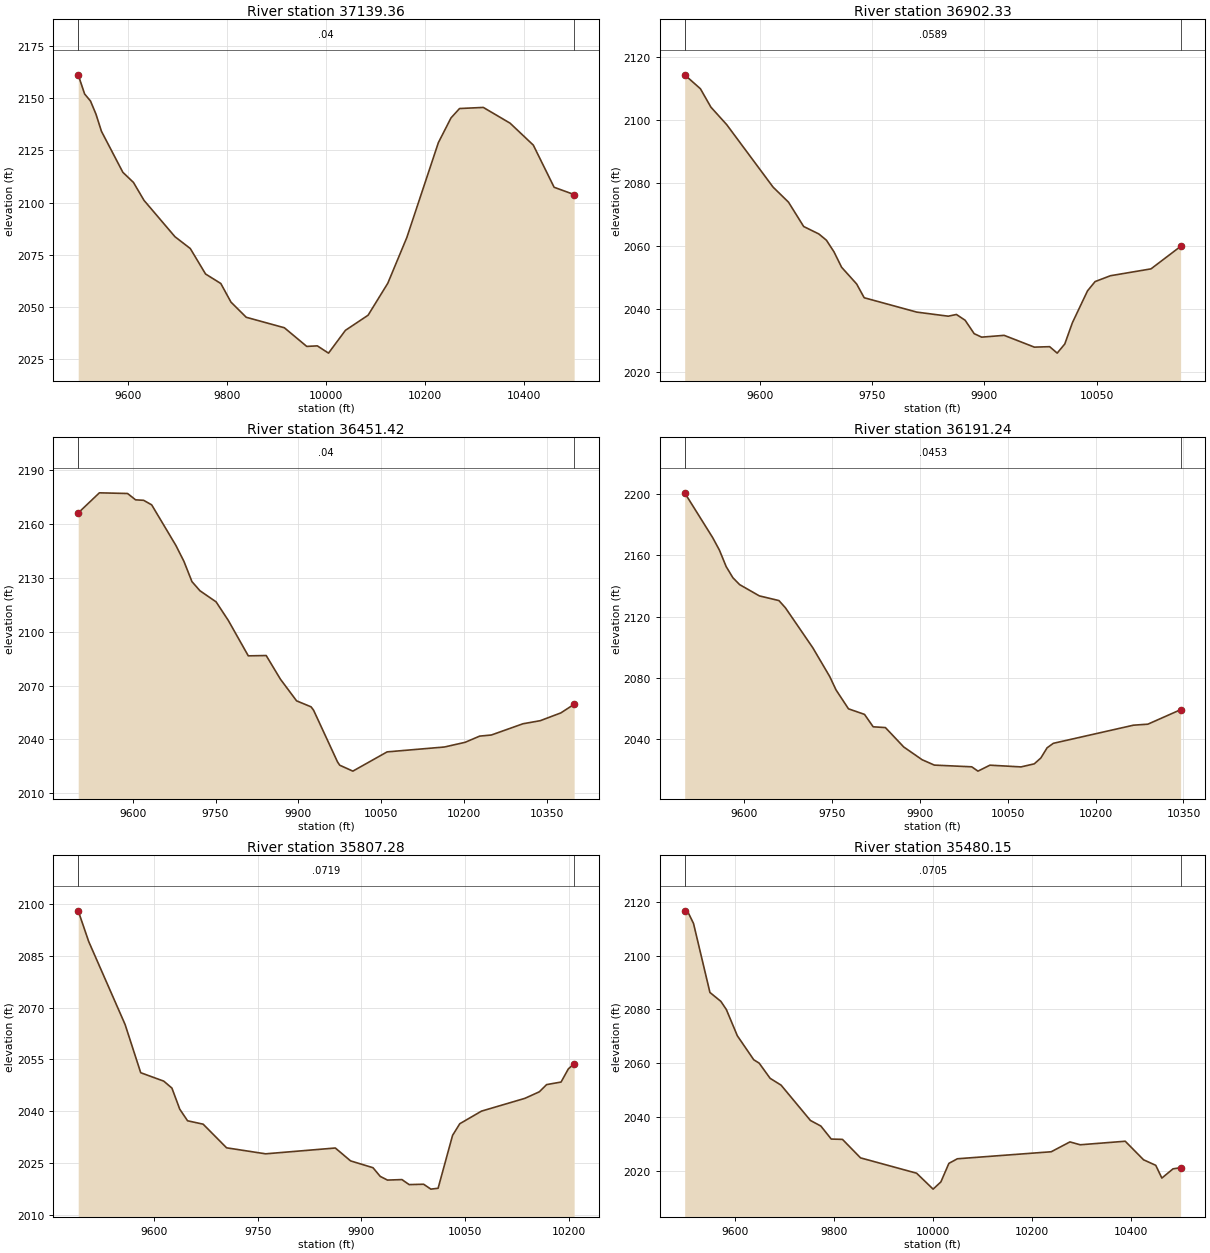
Type RM Length L Ch R = 1 ,37139.36,237.029200,237.029200,237.029200
XS GIS Cut Line= 6
720549.466412064763882.555953714720600.799725919764004.244545498
720677.364410565764264.443971057720818.271963139764374.358675569
720976.785535607764567.283748287721093.893090529764686.651980701
#Sta/Elev= 30
9499.2092161.1749512.1522152.0229524.0362148.6449535.0982142.356 9546.162134.154
9589.4082114.537  9610.82109.696 9632.172101.1079694.6142083.7359725.5962078.078
9756.4142065.9059787.2322061.3489807.7772052.4499838.5952045.1959915.6122040.182
9960.8032031.2589982.1622031.52110004.792028.04610038.962038.95610084.752046.186
10124.552061.48910162.982083.369 10226.72128.74910252.192140.57110269.462145.053
10317.452145.58110371.552138.04110418.452127.54910460.462107.38210500.92 2103.89
#Mann= 3 , 0 , 0
9499.209    0.04       09499.209    0.04       010500.92    0.04       0
#XS Ineff= 2 , 0
       0                               0
Bank Sta=9499.209,10500.92
Exp/Cntr=0.3,0.1

Type RM Length L Ch R = 1 ,36902.33,450.908200,450.908200,450.908200
XS GIS Cut Line= 6
720578.470044997763971.657975706720632.453471513764263.296597148
720611.620081034764328.941499575720544.991064112764419.509014356
720562.156449063764517.266829912720601.391036631764587.836069415
#Sta/Elev= 30
9499.3372114.3129520.3772109.8999534.4122104.0569555.4512098.5379617.5612078.688
9638.1322073.9289658.4482066.2019678.7272063.8399688.8662061.8529699.0052058.155
9709.145 2053.289729.3132047.9629739.333 2043.61 9809.642039.0539851.7312037.757
9862.6722038.3019874.3272036.4659886.4452032.2079896.4062031.1119926.5212031.679
9966.9242027.941 9987.332028.0879997.3972026.04110007.572028.947 10017.72035.673
10037.952045.79110048.082048.734 10068.6 2050.5910122.812052.76410162.432059.891
#Mann= 3 , 0 , 0
9499.337  0.0589       09499.337  0.0589       010162.43  0.0589       0
#XS Ineff= 2 , 0
       0                               0
Bank Sta=9499.337,10162.43
Exp/Cntr=0.3,0.1

Type RM Length L Ch R = 1 ,36451.42,260.179600,260.179600,260.179600
XS GIS Cut Line= 6
719973.719053159763977.063777834720248.107659433764268.404487863
720332.541635751764382.402254216720399.162783564764437.572481605
720459.428039895764514.783768781720594.342383846764620.338190592
#Sta/Elev= 30
9501.2422166.2049539.6172177.4219590.6232177.0529605.2092173.5199619.7942173.249
 9634.38 2170.719678.1372148.1379692.722 2139.279707.3082127.9429721.8932122.815
9751.0642116.6499773.1442106.3229809.4062086.5499841.8282086.7239867.7492073.486
 9896.922061.4619923.131 2058.139927.7072056.2529971.0162027.456 9975.062025.588
9998.8842022.28810060.962033.01410164.752035.73310202.232038.343 10228.7 2041.81
10249.772042.41510307.082048.69210338.33  2050.410375.722054.73910399.822059.556
#Mann= 3 , 0 , 0
9501.242    0.04       09501.242    0.04       010399.82    0.04       0
#XS Ineff= 2 , 0
       0                               0
Bank Sta=9501.242,10399.82
Exp/Cntr=0.3,0.1

Type RM Length L Ch R = 1 ,36191.24,383.961500,383.961500,383.961500
XS GIS Cut Line= 6
719823.263281782764385.948500333720018.760708969764485.392737178
720291.798179985764576.088710943720404.271832495764540.280565159
720445.419145394764541.171175507720589.713516794764641.682410884
#Sta/Elev= 30
9499.0722200.5559546.9322171.3459558.3992163.2229569.8662152.5349581.3332145.283
  9592.82140.8139626.4832133.4689659.8742130.4239670.9062125.7399717.6142099.721
9746.554 2080.979757.2062072.3239778.512 2059.969805.8492056.3439820.6462048.265
 9841.512047.7519872.807 2035.129904.1032026.8379924.9682023.3339988.7572022.216
9999.403 2019.41 10019.82023.28210072.942022.15810095.472024.14910106.662027.962
10117.332034.59210127.97 2037.5110264.622049.30910289.242049.968 10345.12059.403
#Mann= 3 , 0 , 0
9499.072  0.0453       09499.072  0.0453       0 10345.1  0.0453       0
#XS Ineff= 2 , 0
       0                               0
Bank Sta=9499.072,10345.1
Exp/Cntr=0.3,0.1

Type RM Length L Ch R = 1 ,35807.28,327.126200,327.126200,327.126200
XS GIS Cut Line= 4
719934.935133636764578.045011669720236.410076767 764734.69375658
720304.389720798 764703.65957126720593.092240453764790.380099997
#Sta/Elev= 30
9491.0882098.0779506.1732089.2069558.7782065.1159581.3172051.1349614.6142048.689
9626.3942046.6649637.6642040.5659648.9332037.1979671.4722036.208 9705.282029.357
9761.6272027.6149862.261  2029.39884.2462025.5699916.6392023.5859927.0812021.068
9937.5222019.9989958.4052020.1449968.8462018.6899989.7292018.79510000.172017.377
10010.61 2017.6310031.492032.96210041.942036.34510073.262039.99710135.912043.703
10156.792045.60210167.232047.68510188.122048.42610198.562052.21910207.012053.765
#Mann= 3 , 0 , 0
9491.088  0.0719       09491.088  0.0719       010207.01  0.0719       0
#XS Ineff= 2 , 0
       0                               0
Bank Sta=9491.088,10207.01
Exp/Cntr=0.3,0.1

Type RM Length L Ch R = 1 ,35480.15,237.029300,237.029300,237.029300
XS GIS Cut Line= 6
719758.848125837764666.551881985720061.602732793 764817.23139112
720153.270533198764905.979056536720222.220176718764955.135317678
720345.976015738765064.838127942720575.716440587765233.996240079
#Sta/Elev= 30
9499.1312116.6569505.9322116.1229516.9882111.9549550.1562086.2719572.2682082.954
9583.3242079.9189605.4372070.1849638.6052061.2419649.6612059.9639671.7732054.311
9693.885 2051.789753.1922038.6329774.2162036.561 9795.242031.7149817.886  2031.6
9854.3812024.7149967.6612019.008   100012013.082 10016.72015.77610032.862022.667
10049.992024.37810239.592026.99110277.382030.653 10298.12029.58810389.092030.905
10426.082024.00310450.74 2021.9410463.072017.19310485.572020.62610500.952021.067
#Mann= 3 , 0 , 0
9499.131  0.0705       09499.131  0.0705       010500.95  0.0705       0
#XS Ineff= 2 , 0
       0                 10277.6       0
Bank Sta=9499.131,10500.95
Exp/Cntr=0.3,0.1

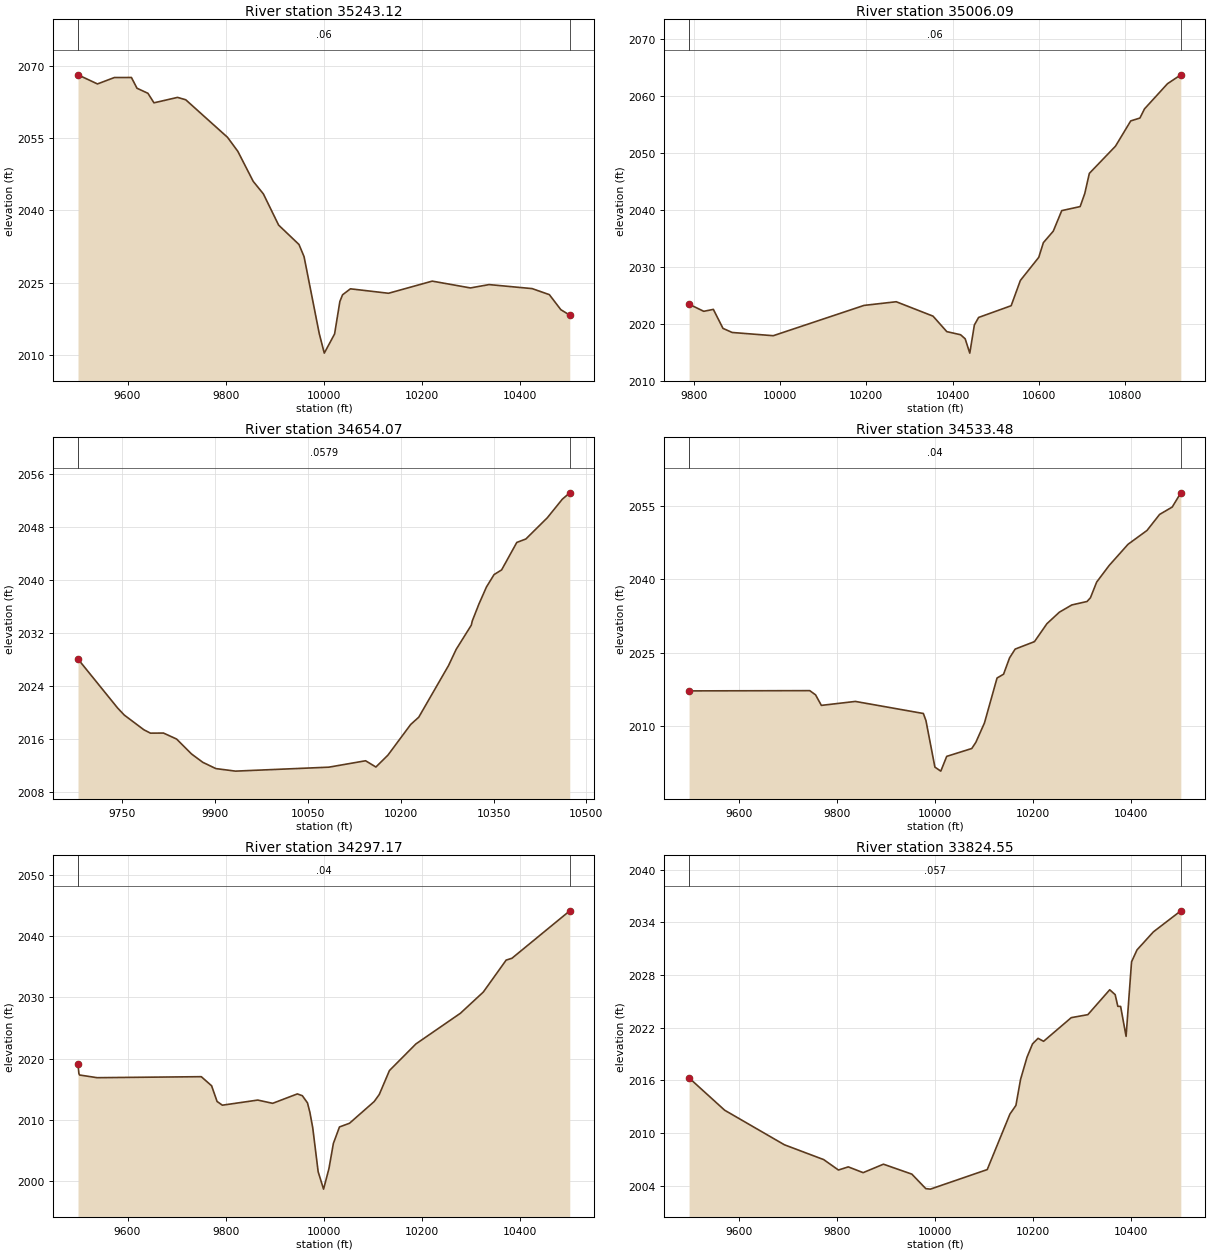
Type RM Length L Ch R = 1 ,35243.12,237.029200,237.029200,237.029200
XS GIS Cut Line= 6
719551.626948751764838.455424106719649.449230552764896.921189267
719755.604396709 764946.06364894720070.843634519765043.102052853
720302.429976703765156.123715878720460.536602062765248.043537713
#Sta/Elev= 30
9499.0462068.1359538.6622066.2449573.2922067.5799607.9042067.582 9619.232065.355
9641.5452064.2999653.8052062.3279701.8452063.4549718.5352062.9619803.6482055.174
9824.6492052.2679855.976 2046.04  9876.72043.4379907.7872036.9589949.2352032.943
9959.5972030.4189990.5822014.43810000.792010.40210021.812014.38510032.552021.119
10038.072022.50610054.032023.74310131.692022.81910220.712025.338 10298.62023.927
10336.492024.62110424.222023.78810459.332022.53510482.742019.41410500.93 2018.28
#Mann= 3 , 0 , 0
9499.046    0.06       09499.046    0.06       010500.93    0.06       0
#XS Ineff= 2 , 0
       0                10354.01       0
Bank Sta=9499.046,10500.93
Exp/Cntr=0.3,0.1

Type RM Length L Ch R = 1 ,35006.09,352.026300,352.026300,352.026300
XS GIS Cut Line= 4
719884.496665657765219.175390452719974.053769529765263.504039258
720219.888069123765186.241830811720953.987878561765457.506269813
#Sta/Elev= 30
9789.0942023.4319823.1292022.1789845.4452022.5159867.7612019.1859889.0212018.468
9984.353  2017.9 10194.82023.21410269.432023.85610354.722021.334 10386.72018.617
10418.682018.06810429.342017.355   104402014.84610450.672019.78810460.492021.103
10535.952023.15910557.272027.58710599.92 2031.6410610.58 2034.2110633.592036.233
10653.222039.83510695.872040.54110706.532042.81110717.192046.35910777.842051.132
10813.142055.55910834.462056.06510845.122057.67210898.422062.08510929.332063.643
#Mann= 3 , 0 , 0
9789.094    0.06       09789.094    0.06       010929.33    0.06       0
#XS Ineff= 2 , 0
       0                10230.03       0
Bank Sta=9789.094,10929.33
Exp/Cntr=0.3,0.1

Type RM Length L Ch R = 1 ,34654.07,120.589300,120.589300,120.589300
XS GIS Cut Line= 4
719825.626716137765194.268873334719911.667411566765445.598273098
720024.878852934 765629.00080809720206.017159045765884.858665526
#Sta/Elev= 30
9678.5752028.1159742.7672020.7149753.3372019.6729785.0462017.4529795.6162016.944
9816.7552016.9579837.8952016.0539861.8892013.8139880.1742012.5479901.3132011.599
9933.0232011.21610083.832011.811 10143.32012.77910159.962011.83610179.362013.623
10216.122018.24610229.192019.34810277.382027.14710289.632029.57110314.13 2033.23
10315.722033.87210326.392036.40410338.642038.99410350.892040.85210363.142041.568
10387.652045.70610402.26 2046.2210436.872049.41710461.16 2052.2210473.242053.185
#Mann= 3 , 0 , 0
9678.575  0.0579       09678.575  0.0579       010473.24  0.0579       0
#XS Ineff= 2 , 0
       0                10126.76       0
Bank Sta=9678.575,10473.24
Exp/Cntr=0.3,0.1

Type RM Length L Ch R = 1 ,34533.48,236.307900,236.307900,236.307900
XS GIS Cut Line= 6
719559.099038853765155.992479253719650.509143886765258.179650264
719705.980597912765329.325945694719802.472801464765497.091232544
719860.540164543765588.892269613720154.437200242765958.594127586
#Sta/Elev= 30
9499.0762017.1729744.9592017.2239756.8022016.3659768.6442014.2049837.9452015.014
9976.4392012.5449981.6522011.1129999.9772001.56110011.972000.74410023.992003.764
10075.112005.37910083.452006.65710100.842010.58910126.572019.80710139.822020.587
10152.112023.945 10163.52025.732 10202.82027.25810228.152030.92810253.492033.283
10278.842034.76510310.012035.48210316.862036.24710329.532039.45510354.872042.838
10393.382047.18310431.992050.01310457.742053.30110483.482054.81610500.982057.724
#Mann= 3 , 0 , 0
9499.076    0.04       09499.076    0.04       010500.98    0.04       0
#XS Ineff= 2 , 0
       0                               0
Bank Sta=9499.076,10500.98
Exp/Cntr=0.3,0.1

Type RM Length L Ch R = 1 ,34297.17,472.615600,472.615600,472.615600
XS GIS Cut Line= 6
719513.137687917765153.572337112719611.193541318765293.850599133
719673.513247419765440.701978704719646.790415542765663.159459531
719660.530028276765740.554457685719838.857035533766054.411658852
#Sta/Elev= 30
9499.1582019.0569500.935 2017.569502.2882017.304 9538.262016.8659750.2562017.029
9771.2962015.5419782.4312012.9739793.1342012.367  9865.32013.2039895.6262012.671
9945.8862014.2119956.0962013.9179966.5622012.7429971.4322011.205 9977.312008.651
9988.303 2001.489999.3021998.63610010.262001.98910019.312006.11310031.752008.809
10052.082009.40710102.462012.964 10112.8 2014.1210133.47 2018.0310187.452022.389
10278.072027.40510324.652030.87110371.232036.10110383.042036.40210500.79 2044.16
#Mann= 3 , 0 , 0
9499.158    0.04       09499.158    0.04       010500.79    0.04       0
#XS Ineff= 2 , 0
       0                               0
Bank Sta=9499.158,10500.79
Exp/Cntr=0.3,0.1

Type RM Length L Ch R = 1 ,33824.55,708.923400,708.923400,708.923400
XS GIS Cut Line= 6
719351.717891288765283.923821043719382.080054808765444.533249038
719383.811682095 765618.15991187719299.317721903765787.175883059
719294.617375655765830.408106136719480.953235387766215.334244214
#Sta/Elev= 30
9499.1452016.2679571.6852012.5839693.3412008.6459773.4212006.9549803.4362005.768
9823.4772006.1259853.7472005.4689895.0592006.4329952.9582005.2989981.3082003.647
9990.685 2003.5910106.452005.818 10152.72012.14410164.882013.13110174.362016.101
10187.432018.618 10198.72020.14410209.972020.77810221.24 2020.4410277.612023.135
10311.432023.47710355.952026.31310367.062025.75510372.432024.42810378.172024.411
10389.282021.003 10400.42029.49510411.512030.85610444.84 2032.9110500.77 2035.31
#Mann= 3 , 0 , 0
9499.145   0.057       09499.145   0.057       010500.77   0.057       0
#XS Ineff= 2 , 0
       0                               0
Bank Sta=9499.145,10500.77
Exp/Cntr=0.3,0.1

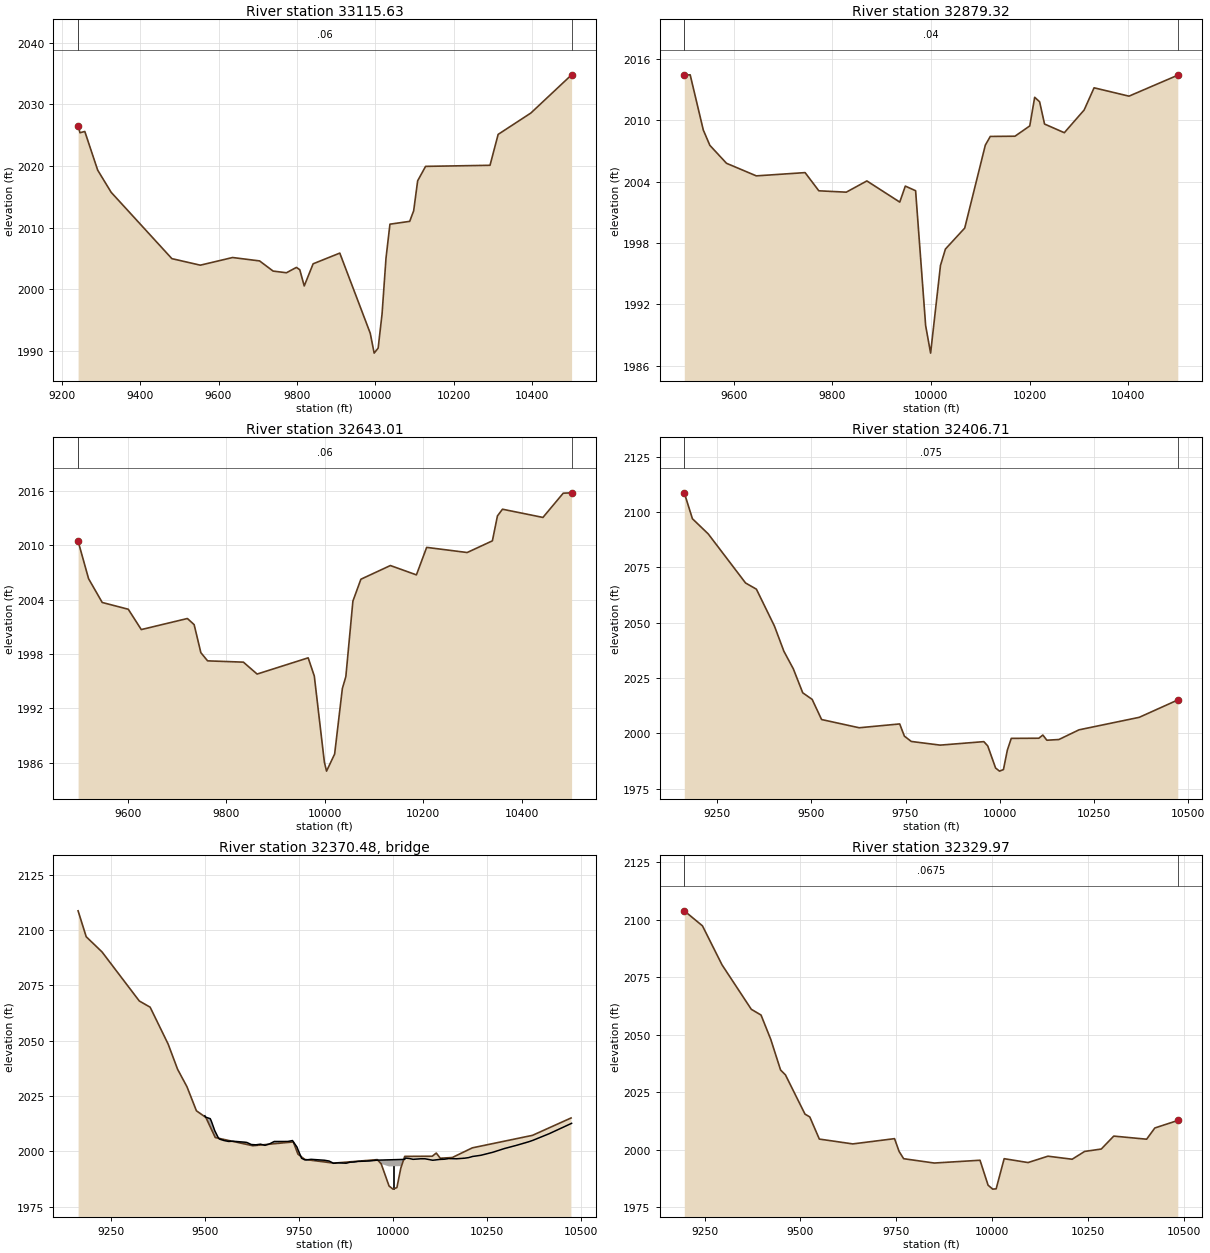
Type RM Length L Ch R = 1 ,33115.63,236.307900,236.307900,236.307900
XS GIS Cut Line= 6
718765.967625231765321.065687656719064.845830381765739.948020577
719166.426634246765929.775084796 719172.95836097766023.761763323
719196.226480445766148.560197732 719282.69620757766443.672743135
#Sta/Elev= 30
9241.5392026.5519246.3722025.3969258.6562025.6059291.5242019.3299325.9582015.727
 9480.912004.9599553.4852003.8999635.8632005.1439704.731 2004.599739.1652002.944
9773.2092002.666 9798.652003.5379807.2772003.1629818.6322000.5299841.3442004.122
9909.3792005.8619987.087 1992.869997.0871989.62410007.291990.44310017.29 1996.01
10027.332005.05310037.372010.554 10087.82011.01310097.942012.73710108.07 2017.59
10128.342019.93710292.732020.11110313.482025.12710396.992028.59510500.932034.796
#Mann= 3 , 0 , 0
9241.539    0.06       09241.539    0.06       010500.93    0.06       0
#XS Ineff= 2 , 0
       0                               0
Bank Sta=9241.539,10500.93
Exp/Cntr=0.3,0.1

Type RM Length L Ch R = 1 ,32879.32,236.307800,236.307800,236.307800
XS GIS Cut Line= 6
718668.433477435765446.020854424718941.267158354765729.002823371
718972.876921382765777.364664388718982.599629395 765838.55900156
718965.803332745766059.893993497719005.660190755766322.248683125
#Sta/Elev= 30
9499.1722014.4459511.1252014.4679537.7492009.0689551.0612007.5679584.8682005.809
9645.3982004.5789744.4072004.8979772.2722003.1179828.0032002.9839869.8012004.082
9936.5462002.013 9947.832003.5799968.7272003.1249989.1081989.9229999.1731987.231
10019.211995.81310029.251997.41610068.42 1999.4710110.242007.585 10120.32008.437
10170.422008.45910200.442009.46710210.452012.26810220.452011.82910230.46 2009.65
10270.612008.80310310.842011.02610331.012013.19710401.89 2012.3810500.942014.432
#Mann= 3 , 0 , 0
9499.172    0.04       09499.172    0.04       010500.94    0.04       0
#XS Ineff= 2 , 0
       0                               0
Bank Sta=9499.172,10500.94
Exp/Cntr=0.3,0.1

Type RM Length L Ch R = 1 ,32643.01,236.307800,236.307800,236.307800
XS GIS Cut Line= 6
718451.052296341765607.947312585 718666.96667747765849.953317436
718827.175160977765982.074722083718863.706425583766024.844617465
718904.649357047766124.964104977718973.933022635766421.490691645
#Sta/Elev= 30
9499.0662010.4489520.3922006.3059548.0452003.6869600.921 2002.949627.3582000.697
9720.9442001.9189734.6192001.2459748.295 1998.15 9761.971997.2489834.6251997.106
9862.4581995.7919966.1441997.5819978.5691995.576    99991986.09210003.411985.087
10019.851986.96910035.521994.19310042.621995.51510056.922003.83310073.162006.249
10133.02 2007.7610185.87 2006.7310206.692009.76210288.882009.19510340.092010.483
10350.342013.22810360.582013.971 10442.72013.065 10483.92015.73810500.882015.778
#Mann= 3 , 0 , 0
9499.066    0.06       09499.066    0.06       010500.88    0.06       0
#XS Ineff= 2 , 0
       0                               0
Bank Sta=9499.066,10500.88
Exp/Cntr=0.3,0.1

Type RM Length L Ch R = 1 ,32406.71,76.733600,76.733600,76.733600
XS GIS Cut Line= 6
718155.276899934765378.162833571718298.958864927765557.352410614
718436.762684375765740.729146734718559.163921237765928.539659813
718628.819976062766161.736091182718760.781683773766521.132407874
#Sta/Elev= 30
9163.0262108.7269184.6072097.0129226.525 2090.169325.6032067.9649354.408 2065.16
9402.2732048.4759427.2912037.1069452.3092029.1669477.3262018.3199502.3442015.328
9527.3622006.2269627.1882002.5079734.6152004.2379747.0661998.7159765.3811996.315
9842.0421994.6549957.8981996.2379968.2951994.2799989.091  1984.39999.488  1982.9
10009.891983.60410020.281992.40110030.681997.707 10103.81997.77510114.461999.218
10125.111996.87510157.07 1997.1910210.332001.56610370.122007.21910472.532015.073
#Mann= 3 , 0 , 0
9163.026   0.075       09163.026   0.075       010472.53   0.075       0
#XS Ineff= 2 , 0
       0                               0
Bank Sta=9163.026,10472.53
Exp/Cntr=0.3,0.1

Type RM Length L Ch R = 3 ,32370.48,,,
BEGIN DESCRIPTION:
END DESCRIPTION:
Bridge Culvert--1,0,-1,-1, 0
Deck Dist Width WeirC Skew NumUp NumDn MinLoCord MaxHiCord MaxSubmerge Is_Ogee
19.994150,36.745300,2.6,0, 60, 60, , , 0.95, 0, 0,0,,
 9499.67 9501.92 9514.06 9517.19 9526.19 9534.83 9538.33 9550.47 9562.61 9574.74
 9605.41 9611.16 9623.30 9635.43 9647.57 9659.71 9671.85 9683.99 9720.40 9732.54
 9744.67 9746.56 9756.81 9764.20 9768.95 9781.84 9817.50 9829.64 9841.78 9853.91
 9875.15 9885.60 9896.06 9906.51 9937.88 9956.86 9956.8610030.7310031.9810043.14
10043.1410052.8910073.8110084.2610105.1710122.7910136.5410147.1210168.5010189.88
10200.5810210.8510232.6510264.7310295.6410328.8810360.9510371.6410414.4110473.93
 2016.07 2015.44 2014.76 2013.55 2009.27 2006.33 2005.55 2004.88 2004.46 2004.55
 2004.13 2004.00 2003.06 2002.94 2003.22 2002.70 2003.38 2004.44 2004.45 2004.87
 2001.87 2000.96 1996.84 1996.22 1996.11 1996.38 1995.96 1995.61 1994.57 1994.80
 1994.61 1995.08 1995.16 1995.42 1995.64 1995.99 1995.99 1996.35 1996.94 1996.75
 1996.75 1996.36 1996.63 1996.63 1995.95 1996.32 1996.43 1996.72 1996.63 1996.89
 1997.16 1997.66 1998.19 1999.57 2001.26 2002.76 2004.36 2005.00 2007.96 2012.65
 1016.07 1015.44 1014.76 1013.55 1009.27 1006.33 1005.55 1004.88 1004.46 1004.55
 1004.13 1004.00 1003.06 1002.94 1003.22 1002.70 1003.38 1004.44 1004.45 1004.87
 1001.87 1000.96  996.84  996.22  996.11  996.38  995.96  995.61  994.57  994.80
  994.61  995.08  995.16  995.42  995.64  995.99 1992.99 1993.35 1993.94 1993.75
  996.75  996.36  996.63  996.63  995.95  996.32  996.43  996.72  996.63  996.89
  997.16  997.66  998.19  999.57 1001.26 1002.76 1004.36 1005.00 1007.96 1012.65
 9499.67 9501.92 9514.06 9517.19 9526.19 9534.83 9538.33 9550.47 9562.61 9574.74
 9605.41 9611.16 9623.30 9635.43 9647.57 9659.71 9671.85 9683.99 9720.40 9732.54
 9744.67 9746.56 9756.81 9764.20 9768.95 9781.84 9817.50 9829.64 9841.78 9853.91
 9875.15 9885.60 9896.06 9906.51 9937.88 9956.86 9956.8610030.7310031.9810043.14
10043.1410052.8910073.8110084.2610105.1710122.7910136.5410147.1210168.5010189.88
10200.5810210.8510232.6510264.7310295.6410328.8810360.9510371.6410414.4110473.93
 2016.07 2015.44 2014.76 2013.55 2009.27 2006.33 2005.55 2004.88 2004.46 2004.55
 2004.13 2004.00 2003.06 2002.94 2003.22 2002.70 2003.38 2004.44 2004.45 2004.87
 2001.87 2000.96 1996.84 1996.22 1996.11 1996.38 1995.96 1995.61 1994.57 1994.80
 1994.61 1995.08 1995.16 1995.42 1995.64 1995.99 1995.99 1996.35 1996.94 1996.75
 1996.75 1996.36 1996.63 1996.63 1995.95 1996.32 1996.43 1996.72 1996.63 1996.89
 1997.16 1997.66 1998.19 1999.57 2001.26 2002.76 2004.36 2005.00 2007.96 2012.65
 1016.07 1015.44 1014.76 1013.55 1009.27 1006.33 1005.55 1004.88 1004.46 1004.55
 1004.13 1004.00 1003.06 1002.94 1003.22 1002.70 1003.38 1004.44 1004.45 1004.87
 1001.87 1000.96  996.84  996.22  996.11  996.38  995.96  995.61  994.57  994.80
  994.61  995.08  995.16  995.42  995.64  995.99 1992.99 1993.35 1993.94 1993.75
  996.75  996.36  996.63  996.63  995.95  996.32  996.43  996.72  996.63  996.89
  997.16  997.66  998.19  999.57 1001.26 1002.76 1004.36 1005.00 1007.96 1012.65
Pier Skew, UpSta & Num, DnSta & Num=  ,10000.00, 2 ,10000.00, 2 , 0 , 0 , 0 ,,
    3.00    3.00
  996.20 1996.20
    3.00    3.00
  996.20 1996.20
BR Coef=-1 , 0 , 0 ,, 0 ,,,0.8,0,1,0,
WSPro=,,,, 1 ,,,, 0 ,,,, 0 ,,,,-1 ,-1 ,-1 , 0 , 0 , 0 , 0 , 0
BC Design=,, 0 ,, 0 ,,,,,,

Type RM Length L Ch R = 1 ,32329.97,390.267200,390.267200,390.267200
XS GIS Cut Line= 6
718093.722078562 765427.74866192 718371.70215705765787.464687914
718466.689440936 765938.07017912718515.902724326766052.245675966
718579.628596693766274.124540925718695.392139167 766548.37805146
#Sta/Elev= 30
 9197.162103.8339244.5512097.3029295.4382080.392 9371.772061.0729397.2132058.563
9422.6572047.9459448.1012034.7129460.8232032.573 9511.712015.5419524.2132014.319
9549.1182004.6989636.2842002.5989745.1082004.8849756.9651999.3339768.8221996.174
9848.7271994.2929967.8561995.5039988.9231984.649   10001 1982.9610009.921983.098
10030.771996.18110092.951994.50210144.781997.26110207.961995.94310240.481999.329
10283.842000.37410316.362005.99210402.022004.64510423.43 2009.5210483.27 2012.78
#Mann= 3 , 0 , 0
 9197.16  0.0675       0 9197.16  0.0675       010483.27  0.0675       0
#XS Ineff= 2 , 0
       0                               0
Bank Sta=9197.16,10483.27
Exp/Cntr=0.3,0.1