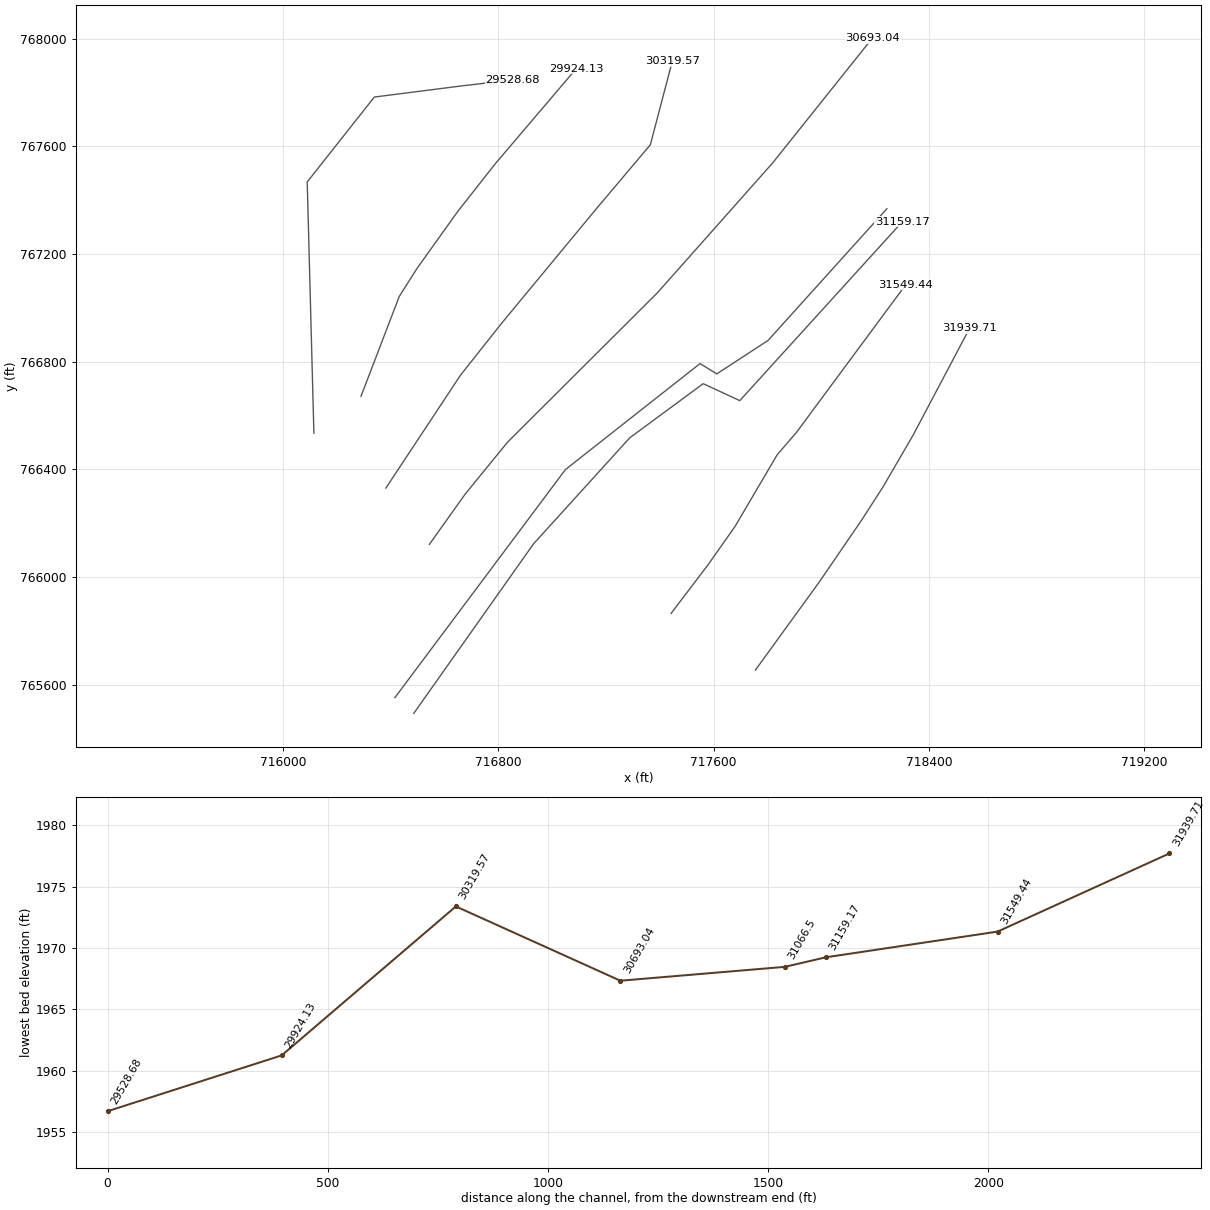
HEC-RAS study 14492_ras.prj: 14492

--- 14492_ras.g01 (geometry) --- (continued)

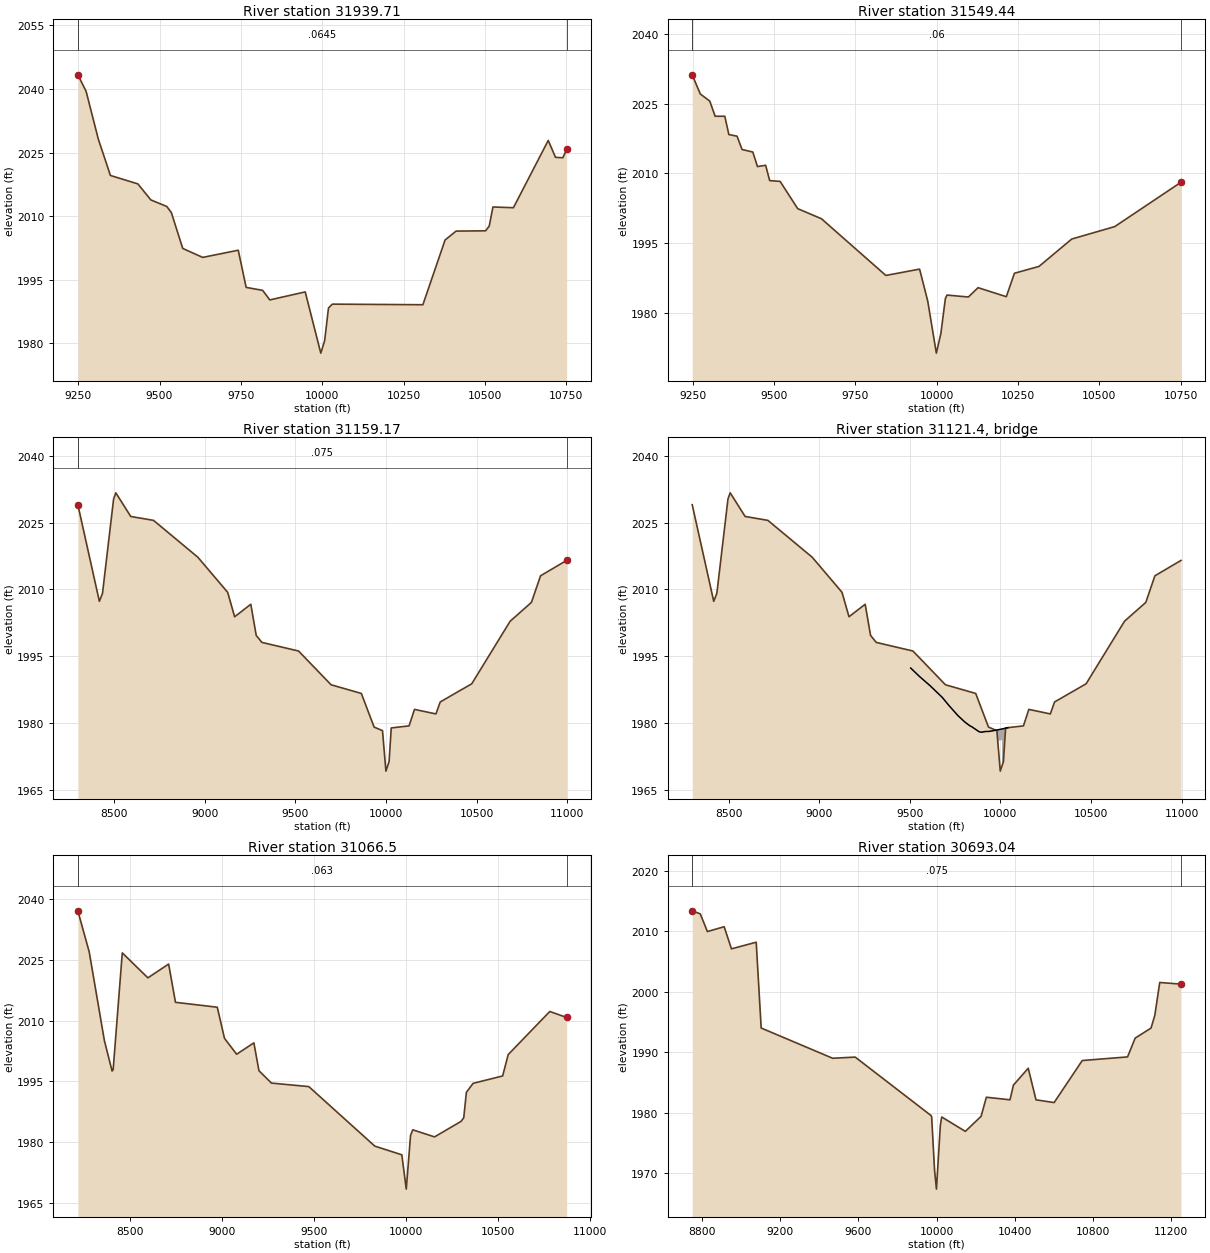
Type RM Length L Ch R = 1 ,31939.71,390.267300,390.267300,390.267300
XS GIS Cut Line= 6
717755.301722165765654.543741491717993.539348767765983.218343099
718150.997480906766213.258521165  718230.0307006766336.298843996
718341.061085005 766527.25737261718551.371273921766925.190783905
#Sta/Elev= 30
9249.0092043.3259274.4492039.4219311.7572028.2019349.0662019.5979433.5362017.602
9473.304 2013.83 9522.332012.2839536.424 2010.839571.3552002.3849632.6372000.275
9741.9522001.9679766.1891993.199 9816.891992.5069838.8981990.2499947.7651992.138
9995.5651977.70210007.431980.64110019.26 1988.36 10031.11989.25410309.331989.114
10377.522004.38210411.452006.47710501.942006.54110513.252007.66210524.56 2012.16
10587.542011.98910694.552027.85710716.84 2023.8710739.462023.77310750.992025.742
#Mann= 3 , 0 , 0
9249.009  0.0645       09249.009  0.0645       010750.99  0.0645       0
#XS Ineff= 2 , 0
       0                10039.62       0
Bank Sta=9249.009,10750.99
Exp/Cntr=0.3,0.1

Type RM Length L Ch R = 1 ,31549.44,390.267200,390.267200,390.267200
XS GIS Cut Line= 6
717442.387317627765865.292263258717580.311352239 766046.92318192
717679.591960567766187.961308044717836.084265893 766454.11623603
717906.189970742766535.224884278718313.705269961767085.930474688
#Sta/Elev= 30
9249.0692031.2399273.8152027.1289302.9962025.5899319.5312022.3199349.1542022.323
 9361.712018.3829386.8232018.0349402.2082015.1679435.279 2014.629449.6052011.491
9474.7182011.767 9487.112008.4739519.1852008.2999573.1782002.4349646.0272000.271
9844.1141988.0559947.7411989.4189972.8371982.5279999.2341971.33410013.131975.558
10026.931983.05810031.991983.83110097.681983.41410127.491985.42210214.221983.482
10239.221988.52810314.661989.99910415.26 1995.8910547.471998.57110750.962008.109
#Mann= 3 , 0 , 0
9249.069    0.06       09249.069    0.06       010750.96    0.06       0
#XS Ineff= 2 , 0
       0                10054.77       0
Bank Sta=9249.069,10750.96
Exp/Cntr=0.3,0.1

Type RM Length L Ch R = 1 ,31159.17,92.671700,92.671700,92.671700
XS GIS Cut Line= 6
716486.445277482765493.779856682716931.377810329766123.472509101
717288.539023995766517.147952944717561.395483464766718.232645318
717697.273390442766655.245205775718300.567665563767319.328583273
#Sta/Elev= 30
8298.3682029.0228417.166 2007.348434.4952009.1428495.7732030.3028508.0172031.686
8590.4562026.3828716.1732025.5068961.0622017.2329125.4632009.3689164.0782003.875
9253.3742006.6839283.139  1999.79314.4941998.1239517.027 1996.199696.5821988.615
9863.711 1986.679934.1911979.1219980.5251978.3269999.2511969.23910016.751971.363
10028.821978.932 10127.31979.39210156.981983.09310275.681982.07310299.051984.756
10473.251988.83710685.472002.88310802.752007.09810853.16 2013.0710997.042016.517
#Mann= 3 , 0 , 0
8298.368   0.075       08298.368   0.075       010997.04   0.075       0
#XS Ineff= 2 , 0
       09919.483        10177.77       0
Bank Sta=8298.368,10997.04
Exp/Cntr=0.3,0.1

Type RM Length L Ch R = 3 , 31121.4,,,
BEGIN DESCRIPTION:
END DESCRIPTION:
Bridge Culvert--1,0,-1,-1, 0
Deck Dist Width WeirC Skew NumUp NumDn MinLoCord MaxHiCord MaxSubmerge Is_Ogee
20.089200,52.493300,2.6,0, 19, 18, , , 0.95, 0, 0,0,,
 9504.61 9554.57 9612.19 9678.58 9715.78 9766.09 9804.68 9830.41 9843.27 9881.86
 9894.72 9919.53 9932.51 9952.85 9988.20 9988.2010008.8710008.8710041.02
 1992.37 1990.43 1988.39 1985.80 1983.97 1981.67 1980.22 1979.44 1979.16 1978.09
 1977.97 1978.14 1978.13 1978.25 1978.53 1978.53 1978.70 1978.70 1978.97
  992.37  990.43  988.39  985.80  983.97  981.67  980.22  979.44  979.16  978.09
  977.97  978.14  978.13  978.25  978.53 1976.03 1976.20  978.70  978.97
 9504.61 9554.57 9612.19 9678.58 9715.78 9766.09 9804.68 9830.41 9843.27 9881.86
 9894.72 9919.53 9932.51 9986.28 9986.2810006.9510006.9510041.02
 1992.37 1990.43 1988.39 1985.80 1983.97 1981.67 1980.22 1979.44 1979.16 1978.09
 1977.97 1978.14 1978.13 1978.51 1978.51 1978.69 1978.69 1978.97
  992.37  990.43  988.39  985.80  983.97  981.67  980.22  979.44  979.16  978.09
  977.97  978.14  978.13  978.51 1976.01 1976.19  978.69  978.97
BR Coef=-1 , 0 , 0 ,, 0 ,,,0.8,0,1,0,
WSPro=,,,, 1 ,,,, 0 ,,,, 0 ,,,,-1 ,-1 ,-1 , 0 , 0 , 0 , 0 , 0
BC Design=,, 0 ,, 0 ,,,,,,

Type RM Length L Ch R = 1 , 31066.5,373.463000,373.463000,373.463000
XS GIS Cut Line= 6
716416.349981278765552.192603484717049.935723692766399.437373459
717549.717691541766792.912567958717611.850286573766754.560627267
717802.083556384766878.698124006718243.483467847767367.910879254
#Sta/Elev= 30
8215.7272037.0398277.7742026.8668360.188 2005.048401.9631997.5728407.7321997.884
8457.4642026.6738596.7842020.5268709.5592023.9268746.8082014.4978974.2592013.285
9013.3892005.6279079.5882001.7019173.3172004.5059200.9381997.6389268.9611994.592
9472.1631993.7299831.2581979.0589978.1831976.921 10002.31968.46410025.721981.704
10037.57 1983.08 10156.21981.33510300.431985.15810314.931986.04310329.431992.323
10366.051994.53110526.69 1996.3510556.832001.61310783.042012.23510874.632010.768
#Mann= 3 , 0 , 0
8215.727   0.063       08215.727   0.063       010874.63   0.063       0
#XS Ineff= 2 , 0
       0  9871.8        10087.06       0
Bank Sta=8215.727,10874.63
Exp/Cntr=0.3,0.1

Type RM Length L Ch R = 1 ,30693.04,373.463100,373.463100,373.463100
XS GIS Cut Line= 6
716544.317935665766121.145263694716676.104903554766306.420410324
716834.034541526766500.147784967717392.294882295767056.797701507
717819.475382359767538.215621535718189.072452961768000.771957048
#Sta/Elev= 30
8749.0492013.339 8790.232012.8398826.7222009.913  8912.62010.7118949.8442007.055
9076.6032008.1519102.0971993.9679467.9671988.9689583.424 1989.169972.0691979.487
9974.8071979.2669989.5841970.4539999.2331967.33510019.251977.89810026.231979.261
10147.211976.88210227.86 1979.3710254.751982.52510375.73  1982.110393.351984.534
10469.091987.31710508.851982.09710601.591981.64210745.591988.59310977.611989.192
11016.341992.29411097.77 1993.9611116.981996.05711142.322001.49711250.982001.221
#Mann= 3 , 0 , 0
8749.049   0.075       08749.049   0.075       011250.98   0.075       0
#XS Ineff= 2 , 0
       0                               0
Bank Sta=8749.049,11250.98
Exp/Cntr=0.3,0.1

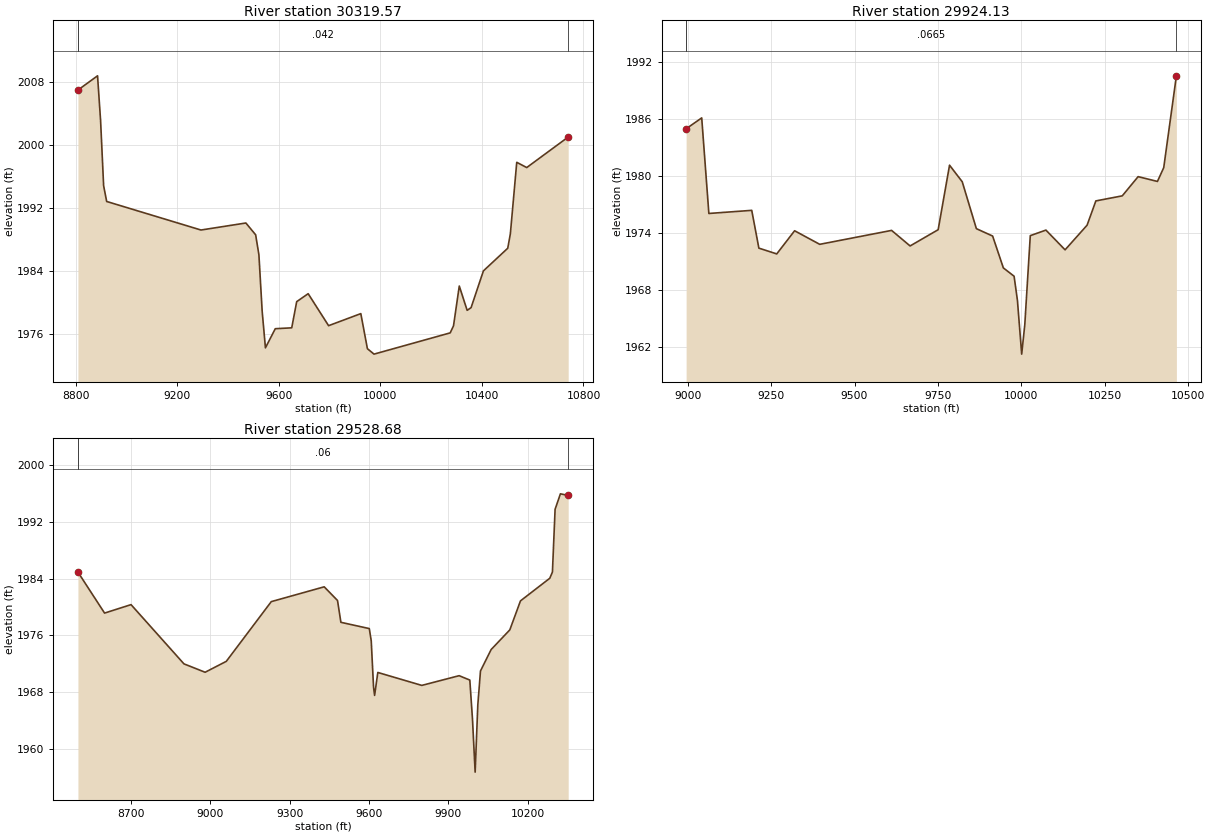
Type RM Length L Ch R = 1 ,30319.57,395.444900,395.444900,395.444900
XS GIS Cut Line= 6
716382.878318489 766330.51660955716660.490575254766750.387673765
716811.813611805766941.400429904717165.072746336767368.540150121
 717365.01888141767605.260481939717446.535907179767915.385720849
#Sta/Elev= 30
8808.0232006.9978885.3272008.8078897.315 2003.118909.303 1994.828921.2911992.815
9292.9251989.1819469.8281990.0749508.3411988.5729521.178 1986.039534.0161978.841
9546.8541974.1859585.666 1976.629650.4881976.7329670.0661980.0669715.3111981.076
9795.7681977.0059922.7421978.5419948.671 1974.089974.6681973.385 10274.91976.089
10287.991976.98810310.721982.05210341.711978.96110357.21  1979.3 10405.8 1983.98
10501.671986.86210512.011988.70110537.161997.799 10576.51997.13210739.892001.016
#Mann= 3 , 0 , 0
8808.023   0.042       08808.023   0.042       010739.89   0.042       0
#XS Ineff= 2 , 0
       09730.513                       0
Bank Sta=8808.023,10739.89
Exp/Cntr=0.3,0.1

Type RM Length L Ch R = 1 ,29924.13,395.445000,395.445000,395.445000
XS GIS Cut Line= 6
716290.519028723766671.353420749716432.487831831767041.897759438
716498.853056937767146.743219316716648.722677946767356.293985188
716789.179653794  767535.0293753717089.749563896767888.079242602
#Sta/Elev= 30
8995.1171984.9529041.8571986.1029063.2751976.0489191.7811976.3769213.1991972.402
9266.7431971.7949320.2871974.2299395.5981972.8029610.9871974.2679666.5341972.632
9750.6051974.3419784.7231981.1269822.7821979.3829865.1331974.4499913.8681973.673
9946.0331970.3229978.1981969.4469988.1921966.91610000.961961.25310010.221964.321
10026.741973.71410073.621974.29910131.011972.22310196.931974.811 10223.31977.369
10302.41  1977.9   103501979.92110407.891979.41710426.721980.86410464.691990.526
#Mann= 3 , 0 , 0
8995.117  0.0665       08995.117  0.0665       010464.69  0.0665       0
#XS Ineff= 2 , 0
       09804.342                       0
Bank Sta=8995.117,10464.69
Exp/Cntr=0.3,0.1

Type RM Length L Ch R = 1 ,29528.68,61.491200,61.491200,61.491200
XS GIS Cut Line= 6
716115.603265792766534.306774363716090.783090532767467.318419874
716339.916503638767782.686698139716668.579449385767824.656307653
716851.968688786 767845.89085117716854.148346305767846.424004808
#Sta/Elev= 30
8499.0881984.9448599.8171979.1558699.8521980.3488899.9231971.9888979.9511970.803
 9059.981972.343 9230.041980.7729430.1111982.8629480.4511980.9339493.1951977.853
9600.5521976.9689607.8891975.2549616.6841968.6889620.6331967.5359632.8161970.773
9799.0481968.9479940.2681970.3199980.5931969.6989990.6741964.20410000.761956.706
10010.84  1966.210020.921970.98410061.241974.01110131.811976.78510172.131980.879
10282.86 1984.0710292.931984.95410302.991993.80810323.131995.98910352.521995.768
#Mann= 3 , 0 , 0
8499.088    0.06       08499.088    0.06       010352.52    0.06       0
#XS Ineff= 2 , 0
       09923.231                       0
Bank Sta=8499.088,10352.52
Exp/Cntr=0.3,0.1