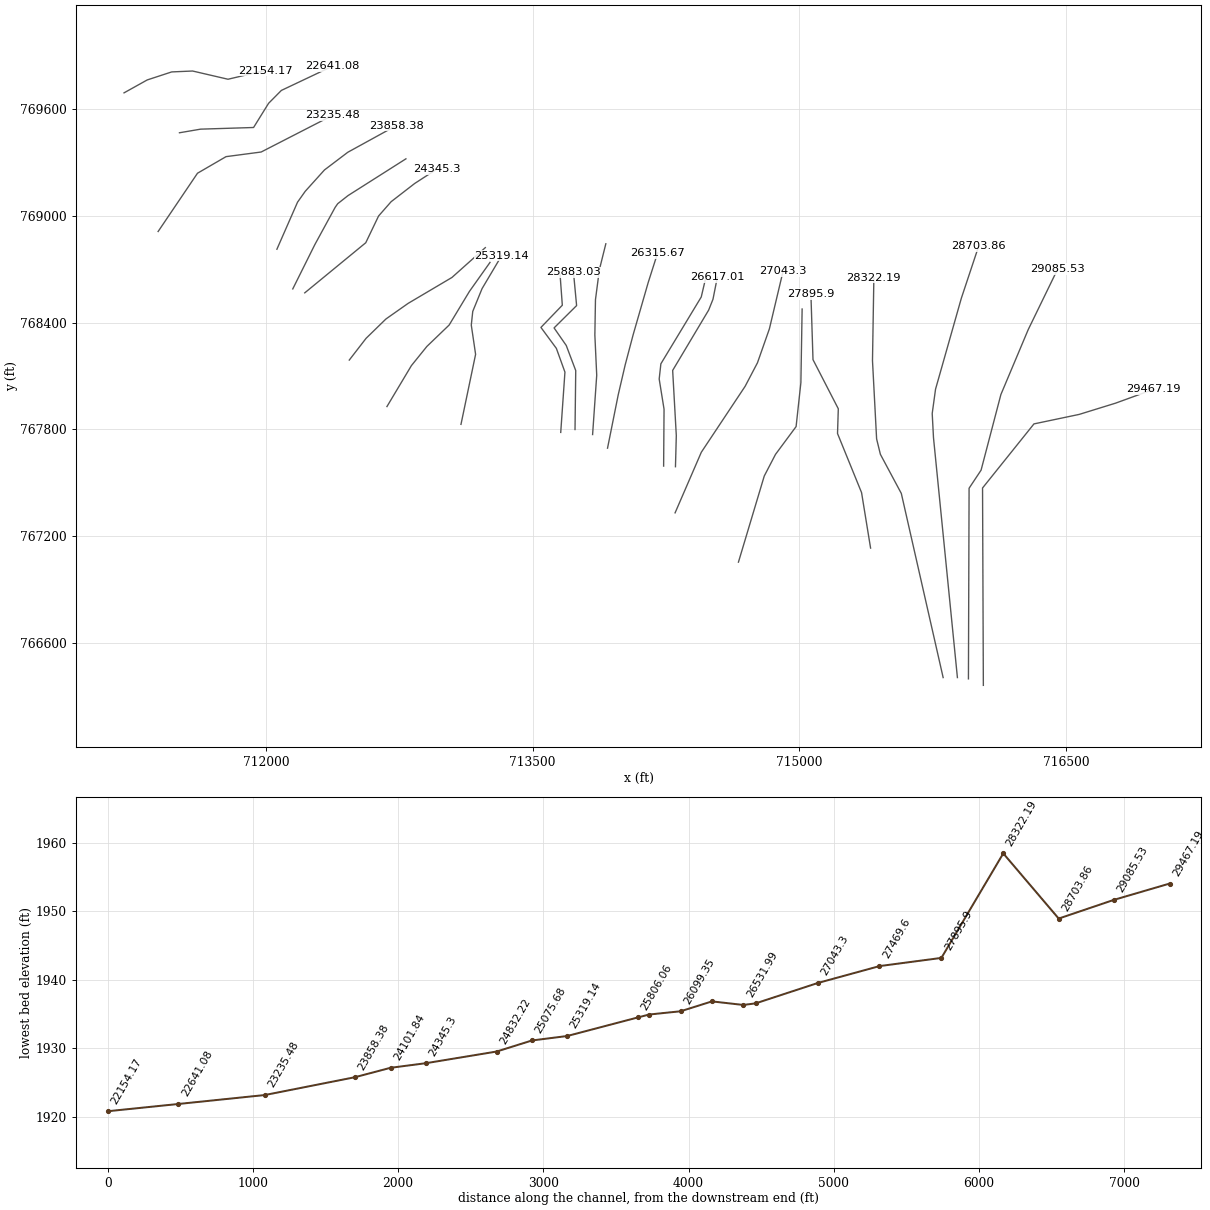
HEC-RAS study 14492_ras.prj: 14492

--- 14492_ras.g01 (geometry) --- (continued)

Type RM Length L Ch R = 3 , 29506.6,,,
BEGIN DESCRIPTION:
END DESCRIPTION:
Bridge Culvert--1,0,-1,-1, 0
Deck Dist Width WeirC Skew NumUp NumDn MinLoCord MaxHiCord MaxSubmerge Is_Ogee
8.435950,44.619300,2.6,0, 41, 41, , , 0.95, 0, 0,0,,
 9848.79 9864.91 9885.01 9895.06 9925.21 9935.26 9957.09 9957.09 9968.7010028.61
10036.4410046.5710048.9510048.9510066.8210076.8610086.9010117.0110127.1710137.48
10147.7810189.0110209.6310219.9410230.2510240.5510250.8610264.2610281.7810302.40
10323.0210343.6310353.9410387.9610405.4810415.7810426.0910436.4010446.7110467.32
10495.24
 1969.42 1969.80 1969.96 1970.18 1970.30 1970.49 1970.67 1970.67 1970.78 1972.45
 1972.84 1973.00 1973.14 1973.14 1974.10 1974.46 1974.96 1976.66 1977.12 1977.76
 1978.61 1981.38 1982.60 1982.95 1983.69 1984.19 1984.84 1985.83 1986.75 1988.25
 1989.26 1990.73 1991.12 1993.16 1994.11 1994.58 1995.23 1995.63 1995.93 1996.32
 1996.52
  969.42  969.80  969.96  970.18  970.30  970.49  970.67 1964.67 1964.78 1966.45
 1966.84 1967.00 1967.14  973.14  974.10  974.46  974.96  976.66  977.12  977.76
  978.61  981.38  982.60  982.95  983.69  984.19  984.84  985.83  986.75  988.25
  989.26  990.73  991.12  993.16  994.11  994.58  995.23  995.63  995.93  996.32
  996.52
 9848.79 9864.91 9885.01 9895.06 9925.21 9935.26 9959.68 9959.68 9968.7010028.61
10036.4410046.5710051.5510051.5510066.8210076.8610086.9010117.0110127.1710137.48
10147.7810189.0110209.6310219.9410230.2510240.5510250.8610264.2610281.7810302.40
10323.0210343.6310353.9410387.9610405.4810415.7810426.0910436.4010446.7110467.32
10495.24
 1969.42 1969.80 1969.96 1970.18 1970.30 1970.49 1970.69 1970.69 1970.78 1972.45
 1972.84 1973.00 1973.30 1973.30 1974.10 1974.46 1974.96 1976.66 1977.12 1977.76
 1978.61 1981.38 1982.60 1982.95 1983.69 1984.19 1984.84 1985.83 1986.75 1988.25
 1989.26 1990.73 1991.12 1993.16 1994.11 1994.58 1995.23 1995.63 1995.93 1996.32
 1996.52
  969.42  969.80  969.96  970.18  970.30  970.49  970.69 1964.69 1964.78 1966.45
 1966.84 1967.00 1967.30  973.30  974.10  974.46  974.96  976.66  977.12  977.76
  978.61  981.38  982.60  982.95  983.69  984.19  984.84  985.83  986.75  988.25
  989.26  990.73  991.12  993.16  994.11  994.58  995.23  995.63  995.93  996.32
  996.52
BR Coef=-1 , 0 , 0 ,, 0 ,,,0.8,0,1,0,
WSPro=,,,, 1 ,,,, 0 ,,,, 0 ,,,,-1 ,-1 ,-1 , 0 , 0 , 0 , 0 , 0
BC Design=,, 0 ,, 0 ,,,,,,

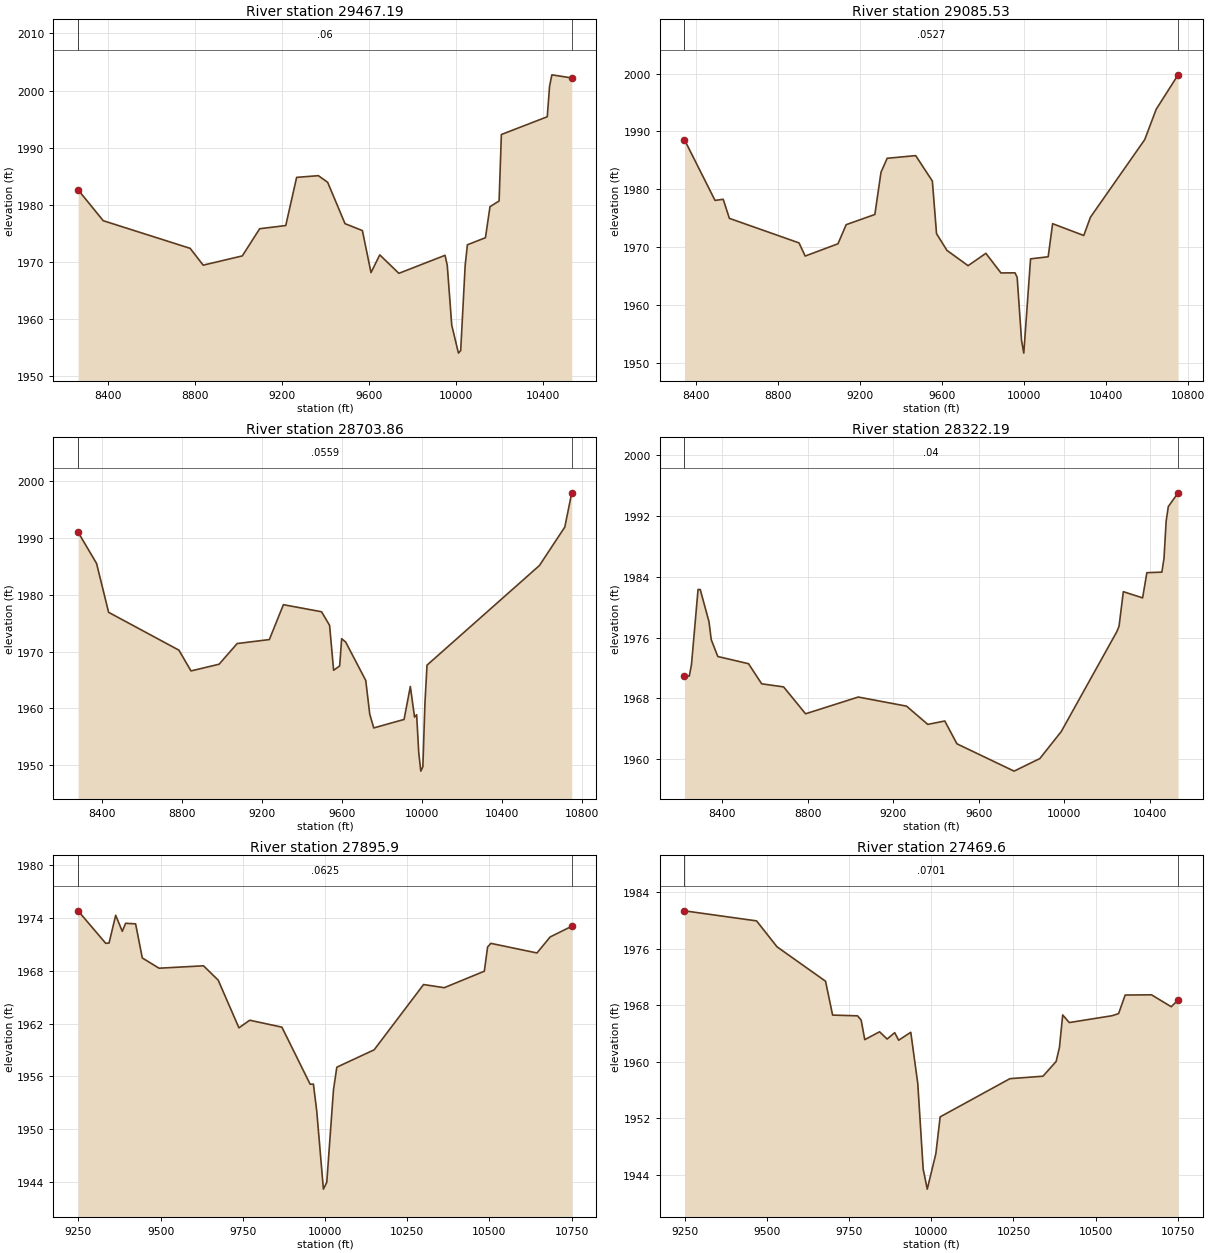
Type RM Length L Ch R = 1 ,29467.19,381.666000,381.666000,381.666000
XS GIS Cut Line= 6
716035.374571025766359.262349382716030.854145974767469.298950776
716320.018399894 767829.71857965716574.171451867767883.081675962
716778.612993002767946.272329599716990.958428174768023.488851458
#Sta/Elev= 30
8260.585 1982.638376.3231977.2218776.3271972.3838836.3271969.4379016.329 1971.06
9096.3291975.816 9216.331976.3769266.3311984.8089366.3321985.1089409.2151983.944
9489.1151976.7029569.0141975.4979608.7111968.1369648.9131971.2419736.9171968.009
9949.3661971.163 9959.661969.3959980.2481958.92810011.131954.03910021.421954.485
10042.011969.395 10052.3 1973.0110135.361974.24210156.291979.67710198.161980.672
10208.631992.31210419.811995.41910430.452000.748 10441.1 2002.7610532.562002.214
#Mann= 3 , 0 , 0
8260.585    0.06       08260.585    0.06       010532.56    0.06       0
#XS Ineff= 2 , 0
       09906.098                       0
Bank Sta=8260.585,10532.56
Exp/Cntr=0.3,0.1

Type RM Length L Ch R = 1 ,29085.53,381.666100,381.666100,381.666100
XS GIS Cut Line= 6
715951.499117374766395.729937911715955.145876229767467.877041012
716022.616511881767569.609167621716134.046826601767994.893374234
716287.419797182768359.362525478716453.303769648768700.555586249
#Sta/Elev= 30
8341.7541988.5738491.0251978.0758531.0251978.2658561.0261974.9728901.0281970.726
8931.0281968.4549091.0291970.5769131.0291973.878 9271.031975.642 9301.031982.927
 9331.031985.3549470.4521985.8149551.6951981.4179572.1151972.3159623.1671969.427
9725.9331966.7929812.8111968.9259886.4591965.5369954.8961965.5529965.5671964.785
9987.0651953.831 9997.891951.67510030.91 1967.97 10116.9 1968.3310138.541974.049
10290.581972.00910323.251975.17210588.151988.58110644.091993.82710750.98 1999.78
#Mann= 3 , 0 , 0
8341.754  0.0527       08341.754  0.0527       010750.98  0.0527       0
#XS Ineff= 2 , 0
       09804.426                       0
Bank Sta=8341.754,10750.98
Exp/Cntr=0.3,0.1

Type RM Length L Ch R = 1 ,28703.86,381.666000,381.666000,381.666000
XS GIS Cut Line= 6
 715889.50421688 766403.02345562715754.963333249767752.171409324
715747.763072282767888.208220646715766.496910959768025.050412834
715911.685966074768536.821280584716008.568329126768827.842889011
#Sta/Elev= 30
 8281.521991.0588373.9481985.5398434.2421976.926 8785.961970.2538846.2551966.593
8986.9421967.7799077.3831971.4249238.1691972.1229308.5051978.2729499.3621977.027
 9539.621974.6249559.7491966.7149589.9421967.4719600.0071972.2789620.1361971.681
9720.4881964.9199740.4941958.966  9760.51956.5489912.0941958.044 9943.581963.861
9964.5711958.4559975.0671958.8779985.527 1952.219995.8531948.93410006.171949.706
 10016.51960.82810026.911967.61610589.241985.17410716.151991.94910750.971997.988
#Mann= 3 , 0 , 0
 8281.52  0.0559       0 8281.52  0.0559       010750.97  0.0559       0
#XS Ineff= 2 , 0
       09851.572                       0
Bank Sta=8281.52,10750.97
Exp/Cntr=0.3,0.1

Type RM Length L Ch R = 1 ,28322.19,426.296500,426.296500,426.296500
XS GIS Cut Line= 6
715809.275522053 766403.02345562715574.035251886767438.573698327
715456.280056059767658.640785664715435.045512557767745.509372756
715411.880555987768185.643547386715419.602208167768650.873091623
#Sta/Elev= 30
 8224.441971.0068246.9771970.9448257.2311972.4318287.996 1982.33 8298.251982.327
8339.269 1978.098349.5241975.7568380.2891973.5218523.8551972.5758585.384 1969.93
8687.9321969.5228790.4791965.9889036.594 1968.199262.1991966.9959361.7111964.595
9441.1031965.0419497.811 1962.049765.0751958.4479885.2411960.1019985.3791963.651
10245.52 1976.8110255.521977.52210275.521982.04710365.53 1981.2310385.531984.542
10455.541984.61710465.551986.41910475.551991.30910485.55 1993.2310531.431995.046
#Mann= 3 , 0 , 0
 8224.44    0.04       0 8224.44    0.04       010531.43    0.04       0
#XS Ineff= 2 , 0
       09918.237                       0
Bank Sta=8224.44,10531.43
Exp/Cntr=0.3,0.1

Type RM Length L Ch R = 1 , 27895.9,426.296500,426.296500,426.296500
XS GIS Cut Line= 6
715401.164278077767131.303934185715350.400237008767443.413712527
715215.228085777767775.593715837 715219.61938646767914.677908373
715077.308704974768191.058768965715065.514068187768560.485750768
#Sta/Elev= 30
9249.1641974.8139333.2071971.1219343.2861971.1539363.4441974.3079383.6021972.486
9393.6811973.3989424.0831973.3329444.4491969.4589495.3821968.2939630.6361968.567
9675.3181966.9369738.3491961.5189771.3231962.3849869.0631961.5959954.8861955.115
9964.8911955.1229974.9461952.0989995.2641943.19210005.521943.95810025.931954.488
 10036.11957.04710149.62 1959.0210299.921966.43710362.851966.07910484.691967.952
10494.711970.71110504.741971.11610644.871970.02510684.941971.84410750.631973.061
#Mann= 3 , 0 , 0
9249.164  0.0625       09249.164  0.0625       010750.63  0.0625       0
#XS Ineff= 2 , 0
       09724.924                       0
Bank Sta=9249.164,10750.63
Exp/Cntr=0.3,0.1

Type RM Length L Ch R = 1 , 27469.6,426.296400,426.296400,426.296400
XS GIS Cut Line= 6
714657.989502948767052.306316082714803.217854213767536.774404394
714866.378965189 767658.25153407714982.236374116 767814.63498984
715009.161134675768061.691949378715016.189009634768475.801672205
#Sta/Elev= 30
9249.1141981.3399468.5731979.9179530.8791976.2499678.3841971.3889699.864  1966.6
9775.6181966.4979786.672 1965.899797.7261963.1299842.6811964.2419865.7151963.215
9888.7491964.1159900.7861963.049 9937.651964.1729958.9541956.9249975.3741944.838
9987.7751941.99710013.891946.99810027.071952.21110239.271957.613 10339.81957.959
 10379.8 1960.04 10389.8    1962 10399.81966.62110419.811965.54310549.821966.508
10569.821966.80710589.821969.43210669.871969.46810730.021967.78210750.871968.743
#Mann= 3 , 0 , 0
9249.114  0.0701       09249.114  0.0701       010750.87  0.0701       0
#XS Ineff= 2 , 0
       0                               0
Bank Sta=9249.114,10750.87
Exp/Cntr=0.3,0.1

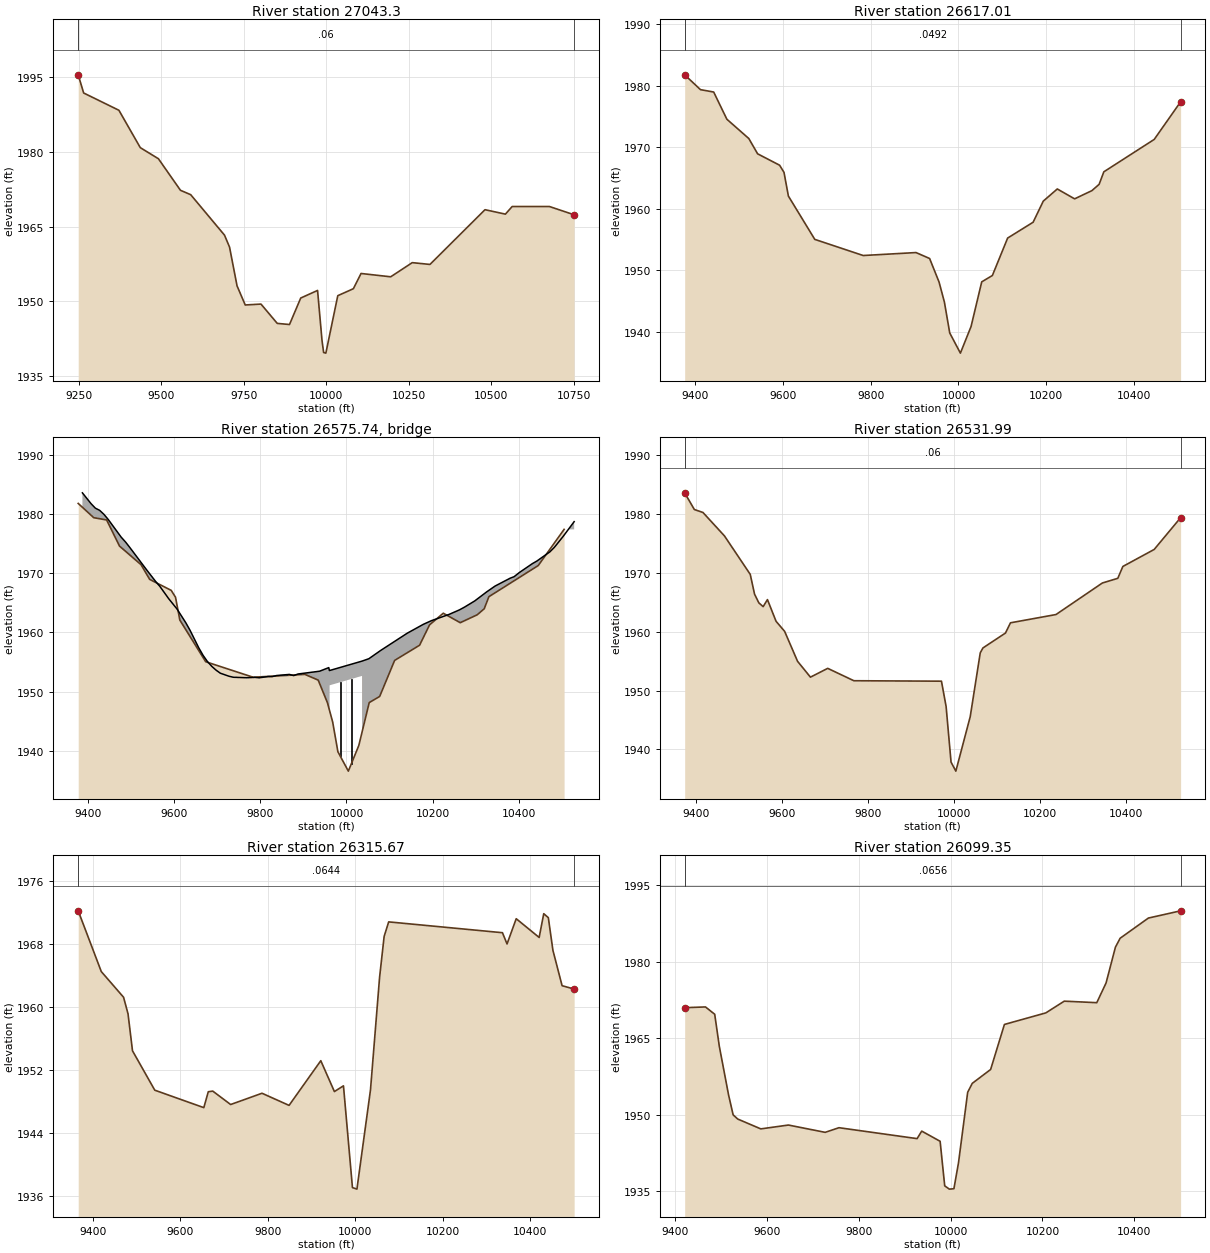
Type RM Length L Ch R = 1 , 27043.3,426.296500,426.296500,426.296500
XS GIS Cut Line= 6
714301.700072902767329.478760918714449.178259672767670.290975805
714695.532716751768041.043627104714764.929737943768173.331394419
714831.950562083768363.988822335 714908.84159806768687.902490913
#Sta/Elev= 30
9249.0451995.5349265.5421991.879 9372.321988.3999437.0651980.8789491.9011978.649
9558.7261972.2949589.6981971.4119692.0441963.2719707.3171960.8679730.0171953.071
9754.8361949.2129802.5791949.3929851.8011945.5089888.9011945.2789922.906 1950.61
9973.8981952.1389987.3481942.0879992.2181939.653    99991939.52110035.121951.082
10082.331952.48510105.581955.55110195.381954.88210260.651957.73210314.281957.372
10480.941968.38910542.731967.49710563.251969.02810676.121969.02810750.931967.364
#Mann= 3 , 0 , 0
9249.045    0.06       09249.045    0.06       010750.93    0.06       0
#XS Ineff= 2 , 0
       09910.245        10153.76       0
Bank Sta=9249.045,10750.93
Exp/Cntr=0.3,0.1

Type RM Length L Ch R = 1 ,26617.01,85.020600,85.020600,85.020600
XS GIS Cut Line= 6
714303.785429537 767588.93077141714308.540141463767763.666435122
714288.017748058768130.540344641714490.407873034768469.741157845
 714514.83725509768530.814612925 714539.14367041768653.986245438
#Sta/Elev= 30
9376.238 1981.79 9412.321979.3779442.3311978.9949472.3421974.5749522.3611971.436
9542.3681968.9559592.466  1967.19602.4891965.9419612.5121962.083 9672.651955.045
9782.9271952.4239903.2061952.904 9934.21 1951.949955.744 1948.119967.8911944.861
9980.0391939.83910004.33 1936.5610028.631940.88710052.921948.14210077.181949.176
10111.971955.26310169.97 1957.8310193.171961.26610225.051963.23910264.521961.634
10303.991962.97110320.331963.994 10331.11966.02810445.861971.29210505.991977.404
#Mann= 3 , 0 , 0
9376.238  0.0492       09376.238  0.0492       010505.99  0.0492       0
#XS Ineff= 2 , 0
       09876.472                       0
Bank Sta=9376.238,10505.99
Exp/Cntr=0.3,0.1

Type RM Length L Ch R = 3 ,26575.74,,,
BEGIN DESCRIPTION:
END DESCRIPTION:
Bridge Culvert--1,0,-1,-1, 0
Deck Dist Width WeirC Skew NumUp NumDn MinLoCord MaxHiCord MaxSubmerge Is_Ogee
28.238700,28.543200,2.6,0, 60, 60, , , 0.95, 0, 0,0,,
 9385.94 9406.08 9416.09 9426.10 9436.11 9446.12 9476.15 9486.16 9496.17 9536.21
 9556.23 9566.23 9586.25 9606.28 9626.39 9636.44 9656.54 9666.59 9676.64 9686.69
 9696.74 9706.79 9726.90 9736.95 9767.10 9787.20 9797.25 9817.35 9827.35 9837.35
 9867.35 9877.35 9887.35 9937.35 9958.84 9960.22 9960.75 9960.7510036.2110036.21
10051.9310079.2610141.1710178.8510197.4710238.5710262.4610274.4010298.2910325.46
10345.7010380.6110389.6210402.0410432.4410442.5710472.9710483.1110503.3710529.34
 1983.58 1981.75 1980.99 1980.62 1979.94 1979.07 1976.09 1975.28 1974.35 1970.48
 1968.61 1967.76 1965.73 1963.92 1961.63 1960.33 1957.39 1956.12 1955.08 1954.27
 1953.62 1953.10 1952.59 1952.42 1952.34 1952.40 1952.33 1952.54 1952.53 1952.71
 1952.90 1952.70 1952.97 1953.44 1954.05 1953.55 1953.56 1953.56 1955.15 1955.15
 1955.55 1956.94 1959.86 1961.37 1961.98 1963.04 1963.80 1964.27 1965.32 1966.82
 1967.84 1969.16 1969.41 1970.12 1971.63 1972.05 1973.61 1974.35 1976.18 1978.71
  983.58  981.75  980.99  980.62  979.94  979.07  976.09  975.28  974.35  970.48
  968.61  967.76  965.73  963.92  961.63  960.33  957.39  956.12  955.08  954.27
  953.62  953.10  952.59  952.42  952.34  952.40  952.33  952.54  952.53  952.71
  952.90  952.70  952.97  953.44  954.05  953.55  953.56 1951.06 1952.65  955.15
  955.55  956.94  959.86  961.37  961.98  963.04  963.80  964.27  965.32  966.82
  967.84  969.16  969.41  970.12  971.63  972.05  973.61  974.35  976.18  978.71
 9385.94 9406.08 9416.09 9426.10 9436.11 9446.12 9476.15 9486.16 9496.17 9536.21
 9556.23 9566.23 9586.25 9606.28 9626.39 9636.44 9656.54 9666.59 9676.64 9686.69
 9696.74 9706.79 9726.90 9736.95 9767.10 9787.20 9797.25 9807.30 9817.35 9827.35
 9837.35 9867.35 9877.35 9887.35 9937.35 9958.84 9960.22 9975.51 9975.5110046.31
10050.9610050.9610079.2610141.1710190.7910238.5710262.4610286.3510298.2910325.46
10345.7010364.1410391.9110402.0410432.4410442.5710472.9710483.1110503.3710529.34
 1983.58 1981.75 1980.99 1980.62 1979.94 1979.07 1976.09 1975.28 1974.35 1970.48
 1968.61 1967.76 1965.73 1963.92 1961.63 1960.33 1957.39 1956.12 1955.08 1954.27
 1953.62 1953.10 1952.59 1952.42 1952.34 1952.40 1952.33 1952.37 1952.54 1952.53
 1952.71 1952.90 1952.70 1952.97 1953.44 1954.05 1953.55 1953.87 1953.87 1955.36
 1955.52 1955.52 1956.94 1959.86 1961.79 1963.04 1963.80 1964.76 1965.32 1966.82
 1967.84 1968.57 1969.52 1970.12 1971.63 1972.05 1973.61 1974.35 1976.18 1978.71
  983.58  981.75  980.99  980.62  979.94  979.07  976.09  975.28  974.35  970.48
  968.61  967.76  965.73  963.92  961.63  960.33  957.39  956.12  955.08  954.27
  953.62  953.10  952.59  952.42  952.34  952.40  952.33  952.37  952.54  952.53
  952.71  952.90  952.70  952.97  953.44  954.05  953.55  953.87 1951.37 1952.86
 1953.02  955.52  956.94  959.86  961.79  963.04  963.80  964.76  965.32  966.82
  967.84  968.57  969.52  970.12  971.63  972.05  973.61  974.35  976.18  978.71
Pier Skew, UpSta & Num, DnSta & Num=  ,9985.40, 2 ,10000.16, 2 , 0 , 0 , 0 ,,
    3.00    3.00
  954.08 1954.08
    3.00    3.00
  954.39 1954.39
Pier Skew, UpSta & Num, DnSta & Num=  ,10011.55, 2 ,10026.31, 2 , 0 , 0 , 0 ,,
    3.00    3.00
  954.63 1954.63
    3.00    3.00
  954.94 1954.94
BR Coef=-1 , 0 , 0 ,, 0 ,,,0.8,0,1,0,
WSPro=,,,, 1 ,,,, 0 ,,,, 0 ,,,,-1 ,-1 ,-1 , 0 , 0 , 0 , 0 , 0
BC Design=,, 0 ,, 0 ,,,,,,

Type RM Length L Ch R = 1 ,26531.99,216.319900,216.319900,216.319900
XS GIS Cut Line= 6
714237.219462395767592.496805355714239.596818358767912.251183182
714212.257224739768082.232134953714221.766648561768167.816949829
714448.804143608768543.439192906714479.709771186 768675.38244915
#Sta/Elev= 30
9373.4121983.5469395.9161980.7139415.9171980.2139465.9191976.2389525.9211969.708
9535.9211966.3519545.9221964.8739555.9221964.2389565.9221965.4269585.9221961.751
9605.9231960.0359635.923 1954.969665.9241952.2689706.0881953.7639766.8591951.662
9970.6071951.5859981.4021947.2859992.9011937.85310004.031936.32410037.491945.569
10060.791956.39310067.071957.226 10119.41959.75310131.13 1961.4910236.911962.893
10344.761968.24410380.711969.04210392.451971.05210465.321973.93910526.771979.329
#Mann= 3 , 0 , 0
9373.412    0.06       09373.412    0.06       010526.77    0.06       0
#XS Ineff= 2 , 0
       09884.439                       0
Bank Sta=9373.412,10526.77
Exp/Cntr=0.3,0.1

Type RM Length L Ch R = 1 ,26315.67,216.319900,216.319900,216.319900
XS GIS Cut Line= 6
713921.699690279767693.236353535713981.915322287767993.599508566
714020.982940017768161.479094885 714065.58417147  768330.4553217
714150.632949926768625.435992728714203.586251634768791.268384965
#Sta/Elev= 30
9366.3851972.1779419.1781964.4659470.1731961.2039480.3721959.0949490.5711954.407
9541.5661949.4059653.755 1947.199663.9541949.2069674.158 1949.299715.1161947.585
9786.8811949.0169848.7591947.4769921.3641953.1489952.481 1949.239973.2261949.959
9993.782 1937.0410004.031936.84410035.04 1949.4410055.851963.73210066.261968.924
10076.671970.77310336.941969.39910347.44 1967.9710368.431971.17610420.921968.798
10431.411971.81310441.911971.30810452.411967.164 10473.41962.67210500.981962.244
#Mann= 3 , 0 , 0
9366.385  0.0644       09366.385  0.0644       010500.98  0.0644       0
#XS Ineff= 2 , 0
       0 9815.88                       0
Bank Sta=9366.385,10500.98
Exp/Cntr=0.3,0.1

Type RM Length L Ch R = 1 ,26099.35,216.319900,216.319900,216.319900
XS GIS Cut Line= 6
713837.732243564767769.856648661713860.922191318768103.340962839
713850.461726943768329.625905808713853.886620102768528.453499668
713875.970088723768697.412417706713912.136969769768842.694381664
#Sta/Elev= 30
9420.8391970.9979466.1621971.1439486.2421969.7099496.2821963.4139516.3611953.908
9526.4011949.9729536.4411949.148 9586.641947.2199646.8041947.9739726.865 1946.54
9756.8881947.4519927.0731945.3099937.0941946.7829977.1781944.7899987.1871936.047
9997.1871935.40110007.191935.47910017.191940.55910037.19  1954.410047.191956.153
10087.191958.875 10117.21967.70810207.381969.97610247.581972.27910318.351971.978
10338.611975.85310358.951982.86410369.191984.61710430.711988.57810500.951989.999
#Mann= 3 , 0 , 0
9420.839  0.0656       09420.839  0.0656       010500.95  0.0656       0
#XS Ineff= 2 , 0
       09750.754                       0
Bank Sta=9420.839,10500.95
Exp/Cntr=0.3,0.1

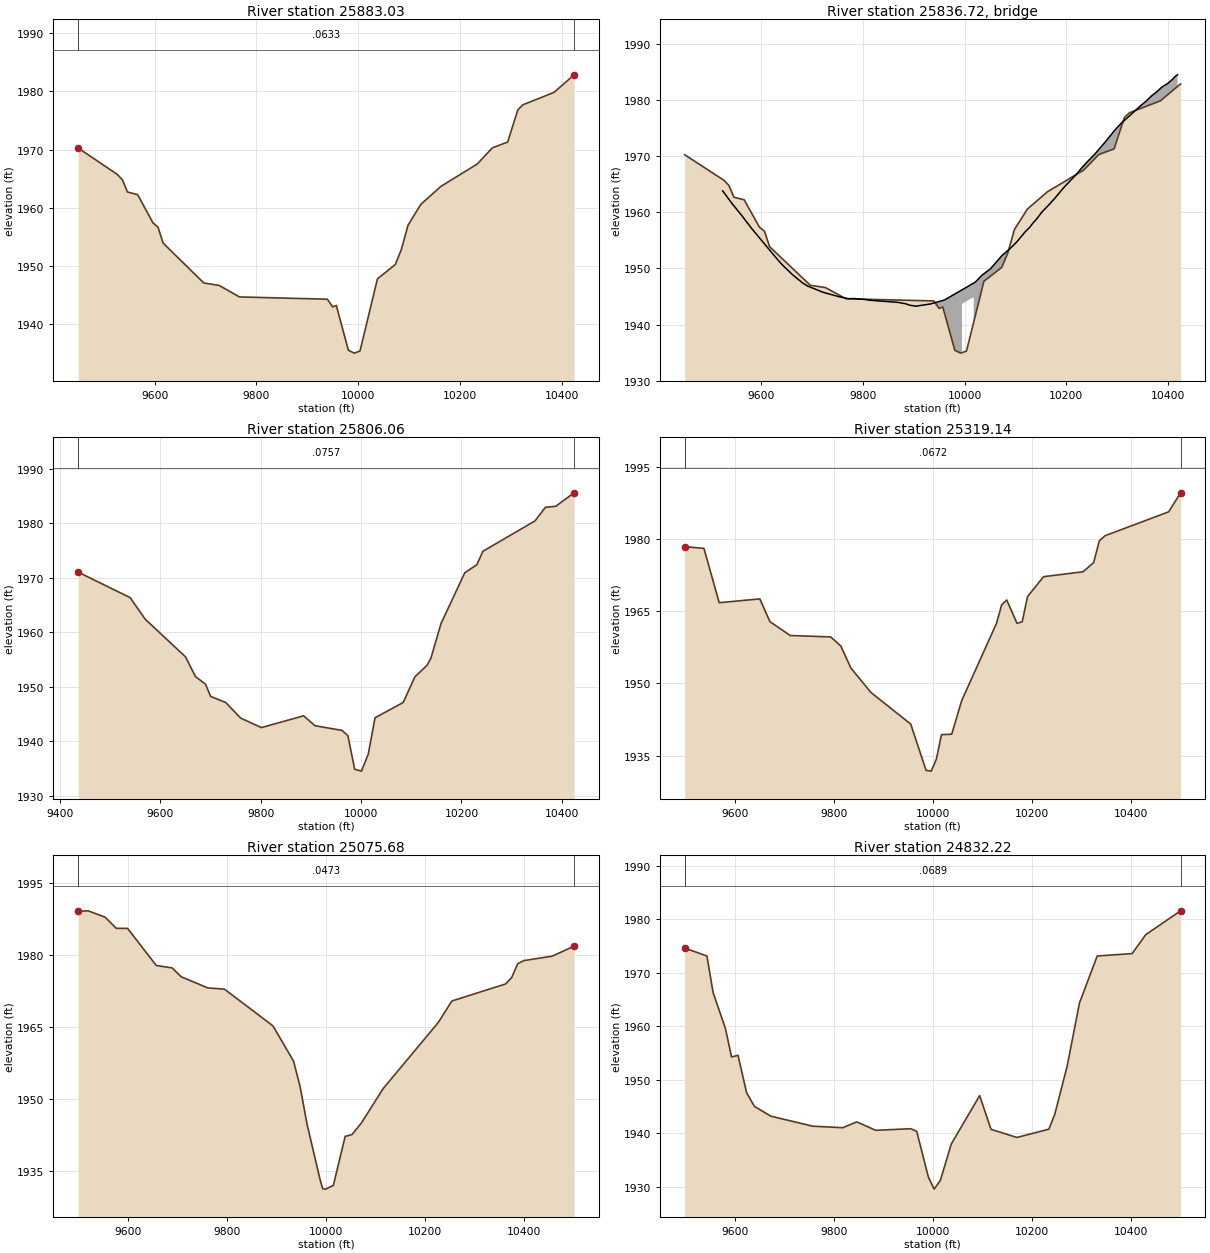
Type RM Length L Ch R = 1 ,25883.03,76.972100,76.972100,76.972100
XS GIS Cut Line= 6
713738.891511316767798.106533154713742.887712181768129.791200817
  713689.5223777768270.861525208713621.051358551 768369.57057029
713747.785782248768495.187229276713730.152729928768683.273120612
#Sta/Elev= 30
9449.7811970.254 9526.681965.711 9536.681964.7819546.6811962.6779566.6831962.228
9596.685 1957.379606.6851956.6189616.6861953.8849696.6921947.0089726.6941946.596
9766.6971944.6089939.5941944.218 9949.97 1942.899957.1811943.1279980.8931935.428
9992.3211934.92910003.751935.28510038.031947.71510073.191950.19610085.181952.807
10098.011956.92210123.291960.548 10162.71963.64110234.221967.50210264.031970.287
10294.031971.28510314.03 1976.8310324.031977.70410385.131979.83910424.751982.864
#Mann= 3 , 0 , 0
9449.781  0.0633       09449.781  0.0633       010424.75  0.0633       0
#XS Ineff= 2 , 0
       0                               0
Bank Sta=9449.781,10424.75
Exp/Cntr=0.3,0.1

Type RM Length L Ch R = 3 ,25836.72,,,
BEGIN DESCRIPTION:
END DESCRIPTION:
Bridge Culvert--1,0,-1,-1, 0
Deck Dist Width WeirC Skew NumUp NumDn MinLoCord MaxHiCord MaxSubmerge Is_Ogee
26.346950,24.278200,2.6,0, 55, 55, , , 0.95, 0, 0,0,,
 9524.49 9541.69 9561.73 9581.76 9631.85 9641.87 9661.90 9681.94 9691.95 9722.04
 9753.85 9772.27 9782.43 9805.06 9813.85 9868.62 9884.82 9891.86 9904.57 9933.41
 9960.61 9995.04 9995.0410018.0110018.0110021.2010034.0310051.1310073.6010089.75
10102.4010119.3110127.7110135.6210140.3710151.9410165.6810178.3310194.1610222.31
10228.1210240.8110255.0010275.0610295.1310307.5110347.5810356.8910367.2210377.55
10387.8710399.8710409.3610414.7210418.72
 1963.81 1961.69 1959.45 1957.08 1951.64 1950.63 1948.88 1947.40 1946.85 1945.75
 1944.96 1944.61 1944.65 1944.48 1944.34 1943.97 1943.70 1943.46 1943.29 1943.69
 1944.39 1946.20 1946.20 1947.41 1947.41 1947.58 1948.78 1949.96 1952.31 1953.56
 1954.70 1956.54 1957.29 1958.21 1958.65 1960.03 1961.32 1962.59 1964.31 1967.01
 1967.68 1968.95 1970.25 1972.35 1974.60 1975.80 1979.09 1979.78 1980.69 1981.43
 1982.28 1982.97 1983.73 1984.24 1984.47
  963.81  961.69  959.45  957.08  951.64  950.63  948.88  947.40  946.85  945.75
  944.96  944.61  944.65  944.48  944.34  943.97  943.70  943.46  943.29  943.69
  944.39  946.20 1943.70 1944.91  947.41  947.58  948.78  949.96  952.31  953.56
  954.70  956.54  957.29  958.21  958.65  960.03  961.32  962.59  964.31  967.01
  967.68  968.95  970.25  972.35  974.60  975.80  979.09  979.78  980.69  981.43
  982.28  982.97  983.73  984.24  984.47
 9524.49 9541.69 9561.73 9581.76 9631.85 9641.87 9661.90 9681.94 9691.95 9722.04
 9753.85 9772.27 9782.43 9805.06 9813.85 9868.62 9884.82 9891.86 9904.57 9933.41
 9960.61 9986.66 9986.6610009.6210009.6210021.2010034.0310051.1310073.6010089.75
10102.4010119.3110127.7110135.6210140.3710151.9410165.6810178.3310194.1610222.31
10228.1210240.8110255.0010275.0610295.1310307.5110347.5810356.8910367.2210377.55
10387.8710399.8710409.3610414.7210418.72
 1963.81 1961.69 1959.45 1957.08 1951.64 1950.63 1948.88 1947.40 1946.85 1945.75
 1944.96 1944.61 1944.65 1944.48 1944.34 1943.97 1943.70 1943.46 1943.29 1943.69
 1944.39 1945.76 1945.76 1946.97 1946.97 1947.58 1948.78 1949.96 1952.31 1953.56
 1954.70 1956.54 1957.29 1958.21 1958.65 1960.03 1961.32 1962.59 1964.31 1967.01
 1967.68 1968.95 1970.25 1972.35 1974.60 1975.80 1979.09 1979.78 1980.69 1981.43
 1982.28 1982.97 1983.73 1984.24 1984.47
  963.81  961.69  959.45  957.08  951.64  950.63  948.88  947.40  946.85  945.75
  944.96  944.61  944.65  944.48  944.34  943.97  943.70  943.46  943.29  943.69
  944.39  945.76 1943.26 1944.47  946.97  947.58  948.78  949.96  952.31  953.56
  954.70  956.54  957.29  958.21  958.65  960.03  961.32  962.59  964.31  967.01
  967.68  968.95  970.25  972.35  974.60  975.80  979.09  979.78  980.69  981.43
  982.28  982.97  983.73  984.24  984.47
BR Coef=-1 , 0 , 0 ,, 0 ,,,0.8,0,1,0,
WSPro=,,,, 1 ,,,, 0 ,,,, 0 ,,,,-1 ,-1 ,-1 , 0 , 0 , 0 , 0 , 0
BC Design=,, 0 ,, 0 ,,,,,,

Type RM Length L Ch R = 1 ,25806.06,486.918700,486.918700,486.918700
XS GIS Cut Line= 6
713658.520577982767781.799387259713682.151643097768120.974674687
713634.062642157768254.327772573713547.165855139768372.358702511
713667.457432806768497.146457314713654.722450614768670.538138375
#Sta/Elev= 30
9436.3141971.0079539.7641966.3419569.8371962.3779650.0311955.483 9670.081951.838
9690.1281950.4499700.1521948.2189730.2251947.0999760.2981944.2229801.3141942.492
9885.4791944.6569908.1681942.8389961.9551941.9779973.7171941.0119987.2321934.839
10000.751934.50510014.261937.61210027.781944.29310083.921947.09910107.031951.775
10131.371953.92210139.051955.19610159.211961.56810206.661970.89910230.691972.372
10242.711974.83710346.551980.414 10367.21982.89710387.861983.10110424.571985.565
#Mann= 3 , 0 , 0
9436.314  0.0757       09436.314  0.0757       010424.57  0.0757       0
#XS Ineff= 2 , 0
       0                               0
Bank Sta=9436.314,10424.57
Exp/Cntr=0.3,0.1

Type RM Length L Ch R = 1 ,25319.14,243.459300,243.459300,243.459300
XS GIS Cut Line= 6
713097.518856458767827.148636039713179.747127865768221.028590563
713155.483673838768385.284150962713163.730975262768462.488541416
713216.024099642768590.521242506713325.905426087768775.595073971
#Sta/Elev= 30
9499.1241978.387 9538.011978.036 9568.831966.7629650.9411967.5489671.4121962.811
9712.3561959.9499794.0911959.6589814.4691957.7759834.847  1953.29875.3451948.121
9955.7331941.557 9986.691931.9489997.0911931.79410007.441934.26410017.851939.371
 10038.51939.46110058.711946.44310129.17 1962.5310139.351966.31410149.591967.316
10170.451962.47210180.961962.81710191.661968.03310224.071972.16310303.851973.181
 10325.11975.07610336.58 1979.5810348.051980.65810476.61 1985.6210500.821989.568
#Mann= 3 , 0 , 0
9499.124  0.0672       09499.124  0.0672       010500.82  0.0672       0
#XS Ineff= 2 , 0
       0                               0
Bank Sta=9499.124,10500.82
Exp/Cntr=0.3,0.1

Type RM Length L Ch R = 1 ,25075.68,243.459400,243.459400,243.459400
XS GIS Cut Line= 6
712681.157892226767927.298960283712818.792061678768157.685134351
712905.650867009768265.330370184713030.888404558768385.699509134
713144.963915896768574.748345503713260.700967022768737.956205122
#Sta/Elev= 30
9499.0551989.0269519.1611989.1249553.2351987.8129575.9521985.4829598.8351985.458
9656.8461977.7259688.6821977.2389707.2981975.3719760.8581973.0629794.4351972.806
9892.3141965.1679933.9681957.8279947.3461952.4939961.3231944.6739987.8731933.032
9992.9831931.212    99991931.13710014.461931.93210038.391942.12310052.151942.508
 10071.11944.91410115.211952.09810226.251965.83510253.861970.33610362.431973.884
10374.691975.21110386.951978.11110399.211978.75410456.481979.67610500.911981.759
#Mann= 3 , 0 , 0
9499.055  0.0473       09499.055  0.0473       010500.91  0.0473       0
#XS Ineff= 2 , 0
       0                               0
Bank Sta=9499.055,10500.91
Exp/Cntr=0.3,0.1

Type RM Length L Ch R = 1 ,24832.22,486.918700,486.918700,486.918700
XS GIS Cut Line= 6
712469.281285435768188.758936711712563.844756572768311.064589204
712675.505981775768419.756881416712800.165586106768507.510359848
713046.756882216768653.316881252713234.444287211768821.092488016
#Sta/Elev= 30
9499.0871974.633 9544.091973.1519556.5081966.3039581.343 1959.619593.8251954.251
9606.8341954.565 9624.291947.5329639.9241945.0139672.928 1943.189757.6621941.304
9818.3761941.0199846.7581942.1089885.1341940.5319956.0511940.8289967.9071940.306
9991.3431931.79710003.011929.52310015.541931.15110037.741937.98110094.991947.028
10117.881940.71910170.281939.19110234.831940.74110246.741943.53610271.661952.501
10296.691964.36610332.471973.15110403.061973.60110430.531977.14810500.951981.603
#Mann= 3 , 0 , 0
9499.087  0.0689       09499.087  0.0689       010500.95  0.0689       0
#XS Ineff= 2 , 0
       0                10083.77       0
Bank Sta=9499.087,10500.95
Exp/Cntr=0.3,0.1

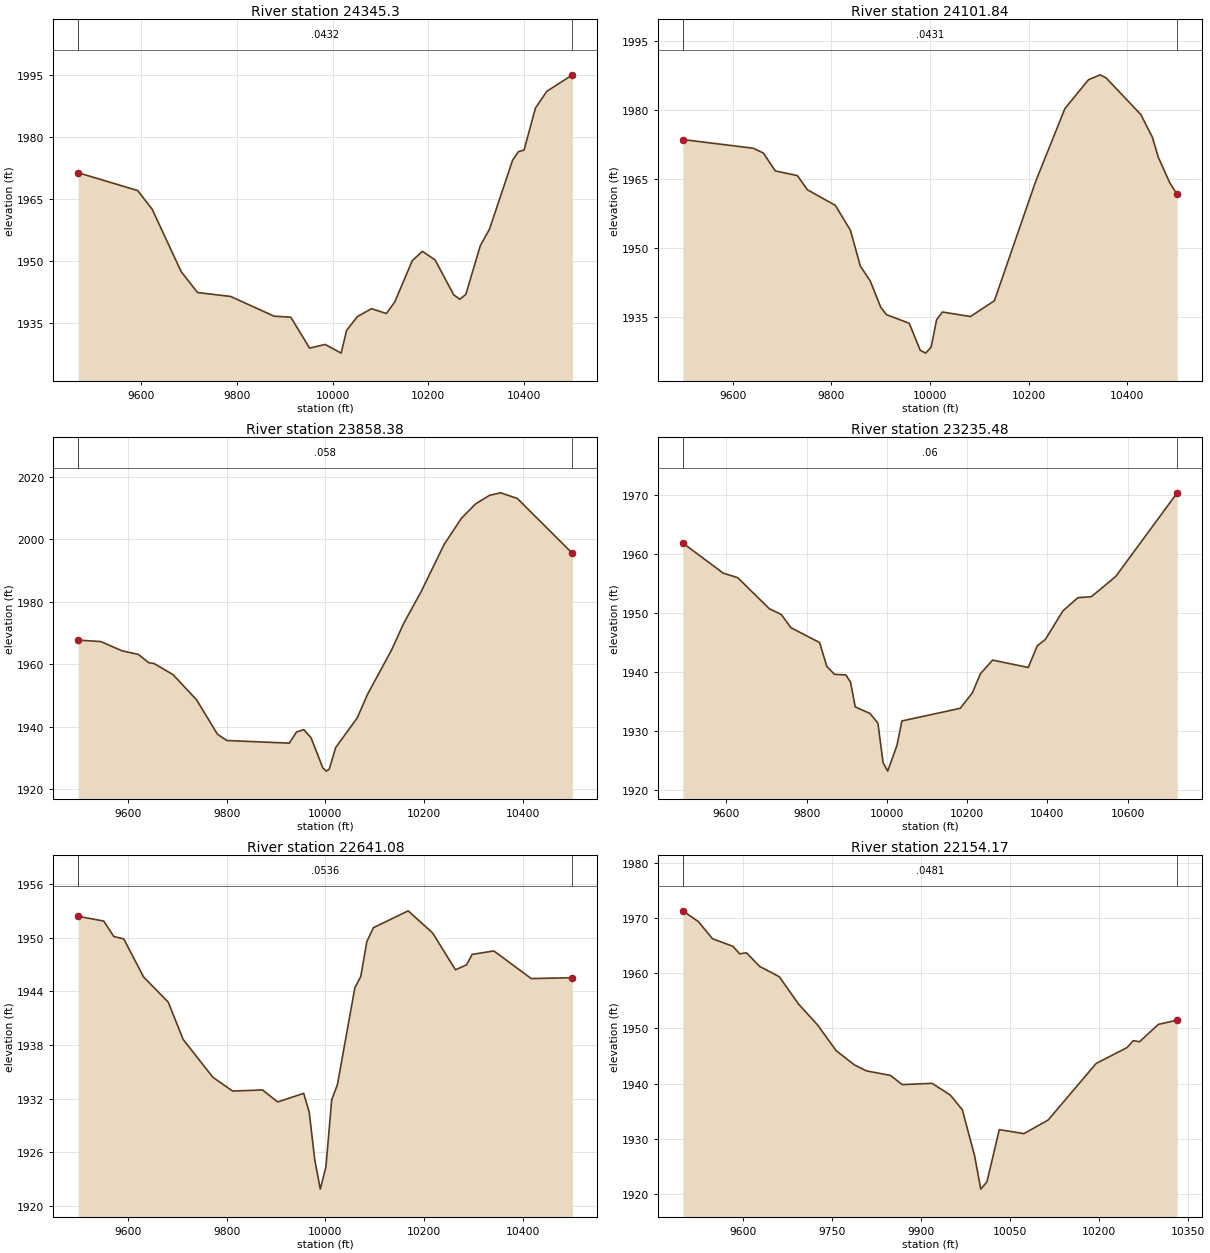
Type RM Length L Ch R = 1 , 24345.3,243.459300,243.459300,243.459300
XS GIS Cut Line= 6
 712218.90444535768566.752726287712561.956425981 768848.56802004
712634.110303959768999.033368858712704.547832941769079.324025732
712837.236660348769181.947384992712959.882994835769261.384904856
#Sta/Elev= 30
9468.7711971.3529593.1341967.0499623.5471962.5039683.726 1947.53 9718.071942.446
9787.2581941.494 9877.851936.7419912.7361936.4959952.0931929.0369984.502 1929.92
10017.971927.82210029.181933.29510051.861936.647 10081.41938.54610112.331937.375
10129.97 1940.1910166.431950.14310187.531952.38810214.161950.30510252.961941.882
10265.741940.82610278.24 1941.9910308.541953.77510327.45 1957.6810375.971974.392
10387.89 1976.43 10399.8 1976.8110423.631986.96610447.461991.00910500.931994.974
#Mann= 3 , 0 , 0
9468.771  0.0432       09468.771  0.0432       010500.93  0.0432       0
#XS Ineff= 2 , 0
       0                 10175.8       0
Bank Sta=9468.771,10500.93
Exp/Cntr=0.3,0.1

Type RM Length L Ch R = 1 ,24101.84,243.459400,243.459400,243.459400
XS GIS Cut Line= 6
 712151.54373583768588.954543598712275.754492601768838.381172784
 712390.11423234769048.023909409712404.439942842769068.332644853
712462.575435094 769114.01654418712787.837730058769320.522992806
#Sta/Elev= 30
9499.0381973.593 9641.391971.713 9662.191970.6699686.2561966.7819731.122 1965.76
9751.5611962.6689808.007 1959.29 9838.721953.8469858.745 1946.069878.6421942.877
9900.0321937.1349911.5991935.5199957.8051933.6469980.0241927.7819991.1341927.151
10002.181928.45110013.261934.39910025.091936.09210081.951935.10910130.371938.549
10213.751964.41110273.311980.33210320.961986.59410344.78 1987.6710356.691987.009
10427.231979.02810450.671974.07410462.391969.78810485.831964.18410500.881961.657
#Mann= 3 , 0 , 0
9499.038  0.0431       09499.038  0.0431       010500.88  0.0431       0
#XS Ineff= 2 , 0
       0                               0
Bank Sta=9499.038,10500.88
Exp/Cntr=0.3,0.1

Type RM Length L Ch R = 1 ,23858.38,622.902500,622.902500,622.902500
XS GIS Cut Line= 6
712062.255903379768812.079953908712178.351496708769076.789822184
712221.370600582769137.640340392712329.698751993 769257.92971016
712461.118617219769357.547656397712733.394360554769507.187921636
#Sta/Elev= 30
9499.075 1967.769545.3521967.268 9588.481964.2879620.827 1963.199642.3911960.503
9653.1731960.2349691.7441956.6449739.2351948.5989781.4281937.5979800.5681935.592
9927.0271934.7439941.7081938.3399956.3891939.059 9971.071936.4789995.0231926.813
10002.241925.78510007.941926.41210021.071933.35110064.92  1942.910085.271950.295
10134.511964.65510158.641973.03510194.65 1983.42 10240.91998.41410275.58 2006.71
10304.652011.38710333.072014.14310355.692014.91710389.212013.09910500.911995.509
#Mann= 3 , 0 , 0
9499.075   0.058       09499.075   0.058       010500.91   0.058       0
#XS Ineff= 2 , 0
       0                               0
Bank Sta=9499.075,10500.91
Exp/Cntr=0.3,0.1

Type RM Length L Ch R = 1 ,23235.48,594.394200,594.394200,594.394200
XS GIS Cut Line= 5
711394.251667619 768911.80480963711615.605834246769239.495781854
711776.196112037769332.811754078711973.678750962769358.853420734
 712375.15444535769565.016615197
#Sta/Elev= 30
9491.6781961.8489592.0761956.7619628.2791955.9849707.394  1950.79736.8881949.741
9760.9891947.4939832.4491944.9799850.3141940.9339869.6331939.5859897.9911939.485
9909.5571938.2359921.1231934.0639957.7931932.9589977.6971931.3029990.5171924.623
10002.081923.17310025.211927.56810037.411931.68210182.611933.82510212.871936.426
10233.041939.685 10263.31942.00110352.231940.75510374.711944.41610394.961945.525
10438.75 1950.3610475.881952.58810509.611952.75610570.091956.17710723.371970.369
#Mann= 3 , 0 , 0
9491.678    0.06       09491.678    0.06       010723.37    0.06       0
#XS Ineff= 2 , 0
       0                               0
Bank Sta=9491.678,10723.37
Exp/Cntr=0.3,0.1

Type RM Length L Ch R = 1 ,22641.08,486.918700,486.918700,486.918700
XS GIS Cut Line= 6
711514.258054239769467.112037906711633.118159704769487.436099346
711931.036790014769496.740767933 712015.45768306769632.701243644
712087.248944662 769705.18817499 712373.07827185769840.612781671
#Sta/Elev= 30
9499.2531952.4199551.2371951.8819571.5081950.1559591.6561949.8899631.8651945.625
9681.8671942.8049711.9741938.6329772.2151934.3979812.2541932.8519872.8161932.976
9903.621 1931.639956.2851932.5959967.4971930.4879978.709 1925.14 9989.92 1921.87
10001.381924.39710012.971931.87410024.591933.56210059.871944.39510071.921945.685
10084.22 1949.5910097.411951.13710167.99 1953.0310217.381950.56110263.73 1946.43
10286.241946.981 10297.51948.15310341.571948.54110417.281945.44610500.871945.543
#Mann= 3 , 0 , 0
9499.253  0.0536       09499.253  0.0536       010500.87  0.0536       0
#XS Ineff= 2 , 0
       0                               0
Bank Sta=9499.253,10500.87
Exp/Cntr=0.3,0.1

Type RM Length L Ch R = 1 ,22154.17,486.918700,486.918700,486.918700
XS GIS Cut Line= 6
711202.461677243769691.573571511711332.820090967769764.172851938
711470.660080446769809.325047215711588.153823866769814.361674411
 711787.29194215769768.134957768711995.214756442769817.255772438
#Sta/Elev= 30
9499.1391971.3799525.583 1969.399549.0481966.3049583.5341964.9289594.7641963.569
9606.3211963.7459628.4521961.2819661.5661959.401 9693.84 1954.459725.8781950.657
9757.2161945.9789787.999 1943.389808.3131942.2939848.5891941.4789868.6021939.804
9918.8021940.0329949.3221937.915 9969.681935.242 9990.391926.86410000.75 1920.81
10011.141922.13410031.931931.61910073.491930.89810114.261933.37310194.991943.643
10247.091946.53410257.611947.79510268.141947.59210299.721950.74710331.521951.519
#Mann= 3 , 0 , 0
9499.139  0.0481       09499.139  0.0481       010331.52  0.0481       0
#XS Ineff= 2 , 0
       0                               0
Bank Sta=9499.139,10331.52
Exp/Cntr=0.3,0.1