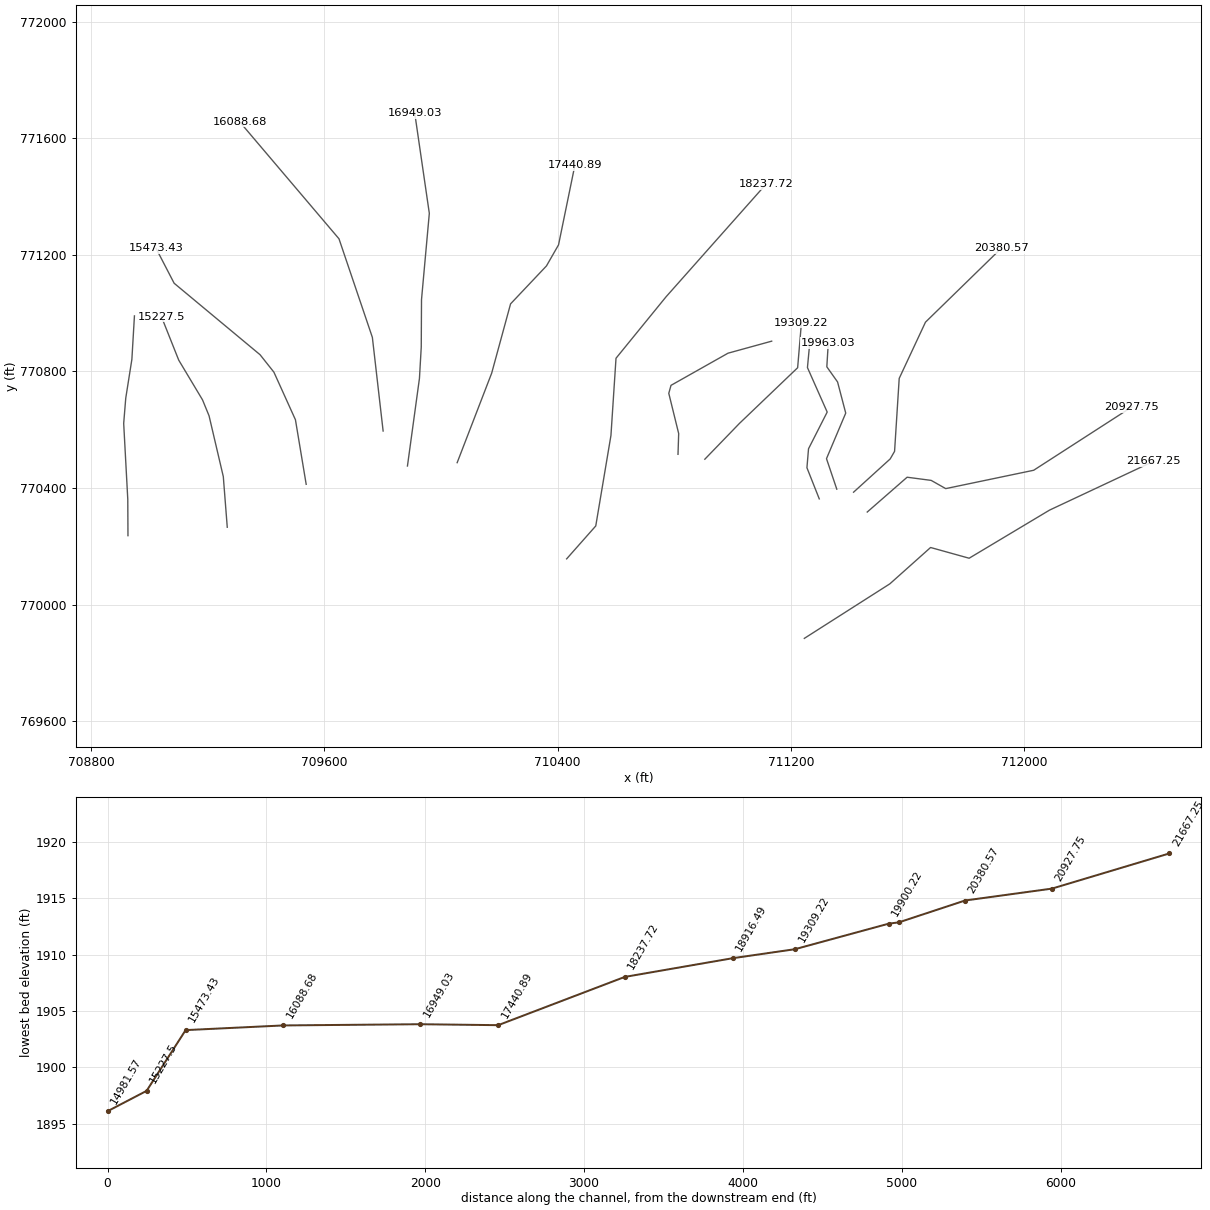
HEC-RAS study 14492_ras.prj: 14492

--- 14492_ras.g01 (geometry) --- (continued)

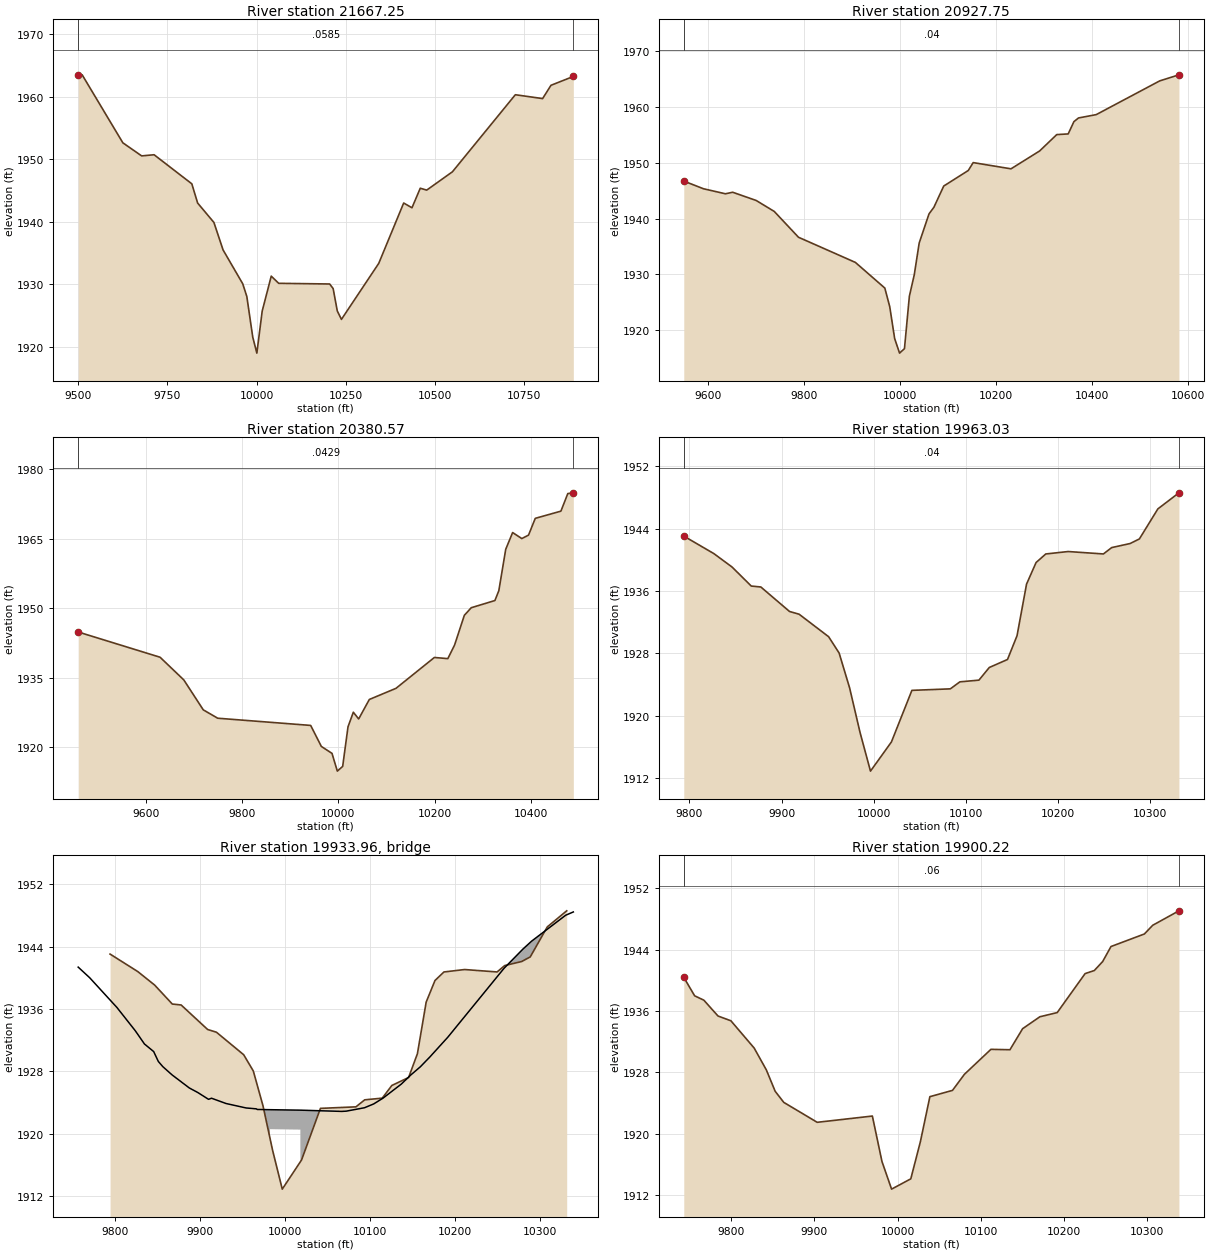
Type RM Length L Ch R = 1 ,21667.25,739.497500,739.497500,739.497500
XS GIS Cut Line= 6
711245.748111248769884.800713614711539.169046372770071.918157533
711678.682905316770196.435516998711810.918334275770159.634670734
712086.525973141770324.565226302712442.428750962770491.665920734
#Sta/Elev= 30
9499.0991963.4819510.3081963.4889624.5531952.6229677.3831950.5259712.369 1950.71
9818.3341946.0639834.6111942.9949880.4461939.8829906.1621935.4869961.3731930.078
9972.8151928.0519989.4991921.549   100011918.994   100161925.71510041.431931.301
10062.361930.15410205.491930.04810215.281929.31610226.941925.73810238.591924.389
10343.471933.353 10413.41942.993 10436.71942.23310460.011945.35710478.121945.055
 10550.31947.98310727.061960.30510803.661959.68910827.191961.81510889.931963.227
#Mann= 3 , 0 , 0
9499.099  0.0585       09499.099  0.0585       010889.93  0.0585       0
#XS Ineff= 2 , 0
       0                               0
Bank Sta=9499.099,10889.93
Exp/Cntr=0.3,0.1

Type RM Length L Ch R = 1 ,20927.75,547.174200,547.174200,547.174200
XS GIS Cut Line= 6
711461.525973171 770318.05480963711598.244723141770437.412448511
711680.710000932770426.561754078 711730.62319535770398.349948511
712032.272500962770461.283976287712368.644028693770678.297865182
#Sta/Elev= 30
9550.3011946.7179591.2731945.3419636.8891944.4399652.0951944.7129700.9341943.241
9738.6041941.2739789.0351936.6449907.4181932.136 9968.711927.5339978.9251924.204
9989.1411918.4939999.3561915.87110009.571916.67410019.791926.082   100301929.927
10040.221935.61410060.651940.83110070.861942.02510091.291945.82510142.371948.611
10152.591950.02710231.291948.913 10290.81952.111 10326.51955.049 10350.31955.169
 10362.21957.37210371.76 1958.0310408.65 1958.6310540.711964.67510580.751965.764
#Mann= 3 , 0 , 0
9550.301    0.04       09550.301    0.04       010580.75    0.04       0
#XS Ineff= 2 , 0
       0                               0
Bank Sta=9550.301,10580.75
Exp/Cntr=0.3,0.1

Type RM Length L Ch R = 1 ,20380.57,417.543700,417.543700,417.543700
XS GIS Cut Line= 6
711414.613965412770386.089032862 711540.22684727770500.179412099
711555.237149817770526.143397883711571.111621594770776.295323454
711661.178750932770969.096476302711921.595417589771223.002726287
#Sta/Elev= 30
9459.6321944.837 9629.72 1939.399679.0741934.4889719.3971928.0419749.452 1926.23
9942.4721924.6789964.6221920.1469986.7731918.6459997.8491914.81510008.921915.832
   100201924.37210031.071927.52610042.151926.075 10064.31930.27810119.681932.681
10199.38 1939.3410227.32 1939.0910241.281942.01310261.591948.43410275.921950.073
10325.081951.62410333.221953.74910347.541962.67810361.871966.29210380.951964.997
10394.921965.74210408.881969.35810462.141970.91310476.461974.70110487.931974.866
#Mann= 3 , 0 , 0
9459.632  0.0429       09459.632  0.0429       010487.93  0.0429       0
#XS Ineff= 2 , 0
       0                               0
Bank Sta=9459.632,10487.93
Exp/Cntr=0.3,0.1

Type RM Length L Ch R = 1 ,19963.03,62.813500,62.813500,62.813500
XS GIS Cut Line= 6
711357.081065953770396.408516333711321.767533064770501.069973201
711387.730326653770657.273532957711359.787754357770764.004997522
711322.918533593770816.030221134711327.906202525 770897.82799159
#Sta/Elev= 30
9793.9091943.0439826.5041940.7989846.3251939.069 9867.131936.6299877.5331936.509
9908.7131933.3629919.0471933.0169951.1171930.125 9962.471928.0379973.8241923.583
9985.1771917.8489996.5311912.87410019.241916.61610041.471923.239 10083.21923.434
10093.531924.33310114.211924.55310125.471926.17710145.221927.20310155.561930.251
10165.89 1936.8810176.231939.64810186.761940.74610211.111941.059 10249.31940.748
10258.291941.56610278.331942.08910288.351942.67810308.381946.52910331.251948.594
#Mann= 3 , 0 , 0
9793.909    0.04       09793.909    0.04       010331.25    0.04       0
#XS Ineff= 2 , 0
       09934.771                       0
Bank Sta=9793.909,10331.25
Exp/Cntr=0.3,0.1

Type RM Length L Ch R = 3 ,19933.96,,,
BEGIN DESCRIPTION:
END DESCRIPTION:
Bridge Culvert--1,0,-1,-1, 0
Deck Dist Width WeirC Skew NumUp NumDn MinLoCord MaxHiCord MaxSubmerge Is_Ogee
20.251900,22.309700,2.6,0, 36, 36, , , 0.95, 0, 0,0,,
 9756.37 9769.88 9801.96 9823.58 9834.39 9845.20 9850.70 9856.01 9866.82 9887.12
 9897.20 9909.76 9913.30 9930.46 9954.08 9965.89 9967.11 9982.12 9982.1210017.88
10017.8810066.4110071.6910093.3110104.1210114.9310136.5510147.7310158.9510170.17
10191.3910257.4510279.8810289.9210330.0610339.04
 1941.37 1940.01 1936.19 1933.20 1931.50 1930.53 1929.26 1928.59 1927.54 1925.86
 1925.27 1924.40 1924.54 1923.86 1923.29 1923.18 1923.10 1923.07 1923.07 1923.01
 1923.01 1922.85 1922.88 1923.32 1923.81 1924.54 1926.35 1927.52 1928.57 1929.83
 1932.38 1941.21 1943.70 1944.70 1948.03 1948.45
  941.37  940.01  936.19  933.20  931.50  930.53  929.26  928.59  927.54  925.86
  925.27  924.40  924.54  923.86  923.29  923.18  923.10  923.07 1920.57 1920.51
  923.01  922.85  922.88  923.32  923.81  924.54  926.35  927.52  928.57  929.83
  932.38  941.21  943.70  944.70  948.03  948.45
 9756.37 9769.88 9801.96 9823.58 9834.39 9845.20 9850.70 9856.01 9866.82 9887.12
 9897.20 9909.76 9913.30 9930.46 9954.08 9965.89 9967.11 9982.12 9982.1210017.88
10017.8810066.4110071.6910093.3110104.1210114.9310136.5510147.7310158.9510170.17
10191.3910257.4510279.8810289.9210330.0610339.04
 1941.37 1940.01 1936.19 1933.20 1931.50 1930.53 1929.26 1928.59 1927.54 1925.86
 1925.27 1924.40 1924.54 1923.86 1923.29 1923.18 1923.10 1923.07 1923.07 1923.01
 1923.01 1922.85 1922.88 1923.32 1923.81 1924.54 1926.35 1927.52 1928.57 1929.83
 1932.38 1941.21 1943.70 1944.70 1948.03 1948.45
  941.37  940.01  936.19  933.20  931.50  930.53  929.26  928.59  927.54  925.86
  925.27  924.40  924.54  923.86  923.29  923.18  923.10  923.07 1920.57 1920.51
  923.01  922.85  922.88  923.32  923.81  924.54  926.35  927.52  928.57  929.83
  932.38  941.21  943.70  944.70  948.03  948.45
BR Coef=-1 , 0 , 0 ,, 0 ,,,0.8,0,1,0,
WSPro=,,,, 1 ,,,, 0 ,,,, 0 ,,,,-1 ,-1 ,-1 , 0 , 0 , 0 , 0 , 0
BC Design=,, 0 ,, 0 ,,,,,,

Type RM Length L Ch R = 1 ,19900.22,591.000300,591.000300,591.000300
XS GIS Cut Line= 6
711296.982655168770363.149882346711254.713349909770469.863261312
711260.138697118770534.967427984711324.157794356770660.835483551
711256.449461013770813.396247417711266.087965459770916.070818171
#Sta/Elev= 30
9743.3891940.3939756.455 1937.989767.4811937.4169784.4831935.3489799.9771934.723
9827.8591931.1739842.4811928.3239853.1071925.529 9863.43 1924.089903.5681921.479
9969.7841922.2969981.3191916.3639992.8541912.76210015.921914.10510027.421918.945
10038.831924.823   100661925.64610080.291927.74110112.111930.99910134.951930.947
10150.181933.69510170.871935.24910191.651935.79310225.191940.88210236.191941.278
10246.211942.44710256.231944.41110296.331946.04910306.351947.186 10337.8 1949.07
#Mann= 3 , 0 , 0
9743.389    0.06       09743.389    0.06       0 10337.8    0.06       0
#XS Ineff= 2 , 0
       09950.909                       0
Bank Sta=9743.389,10337.8
Exp/Cntr=0.3,0.1

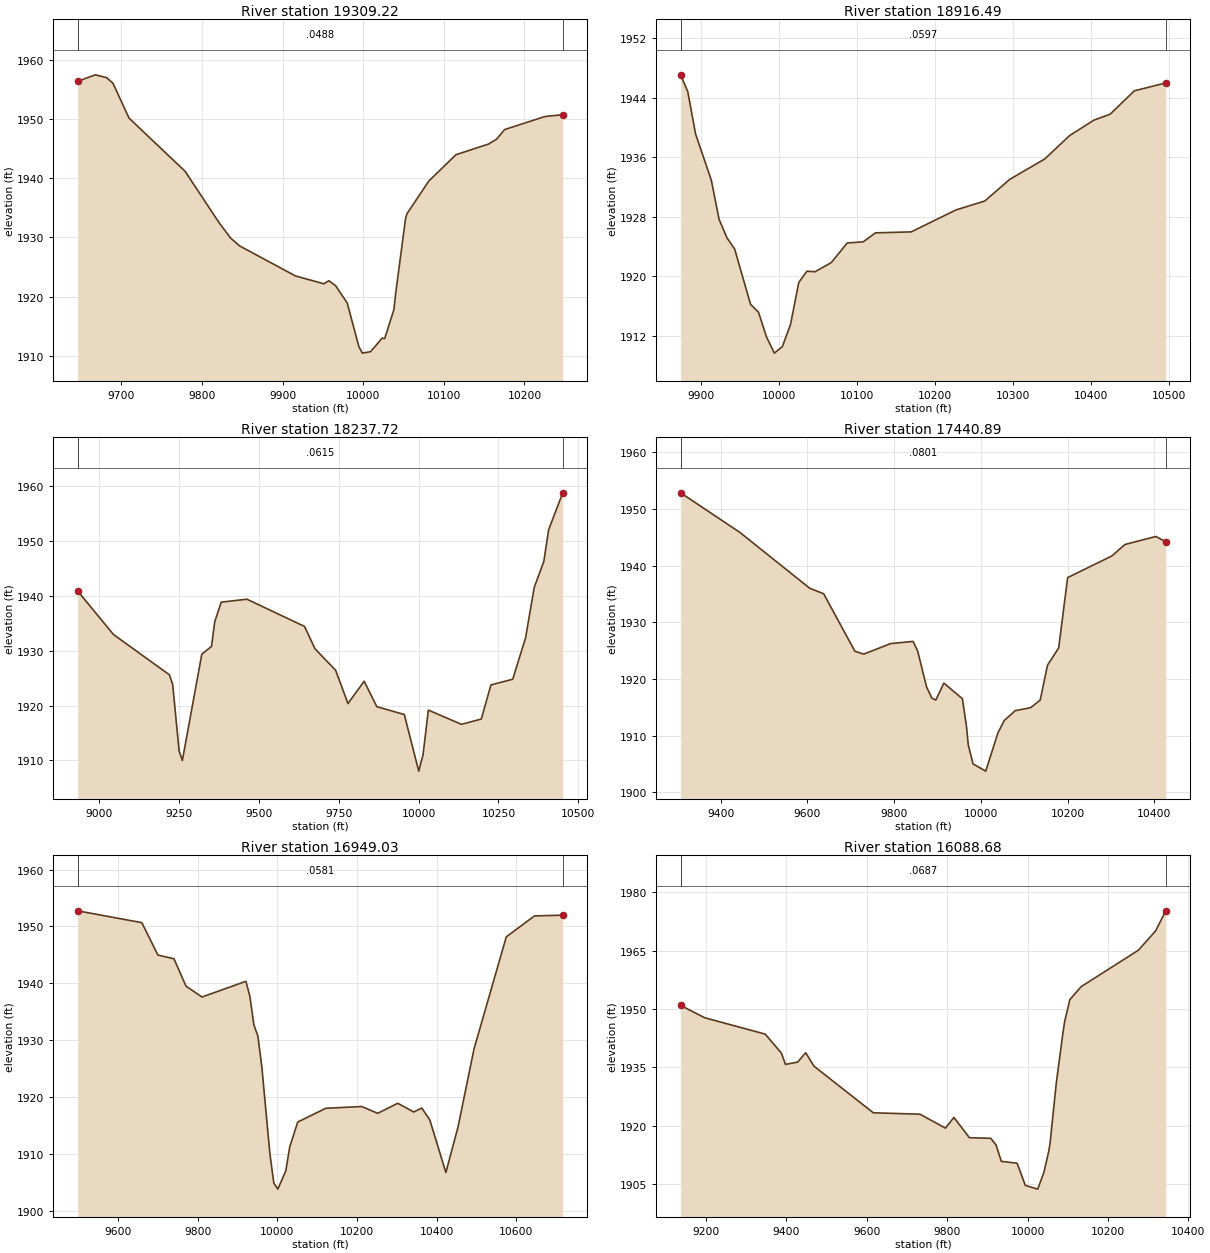
Type RM Length L Ch R = 1 ,19309.22,392.729500,392.729500,392.729500
XS GIS Cut Line= 4
710904.593008933770499.215916758711023.157917589770621.874254063
 711222.81069538770812.846476302711235.831528693770966.926337406
#Sta/Elev= 30
9646.0041956.3419667.9561957.4379681.8651956.9599689.7541956.0249709.6811950.134
9779.2221941.1689821.1211932.5389835.5881929.9119846.8241928.5789916.0151923.515
9951.325 1922.199957.5291922.7049965.7921921.8799980.2591918.9519994.7261911.569
9999.0431910.49410009.191910.74310023.661913.03210026.721912.95210038.131917.831
10040.561920.81210052.591933.218 10054.41934.01610081.53 1939.5410115.111943.964
10155.261945.74710165.291946.56110175.331948.19910225.511950.40710247.511950.711
#Mann= 3 , 0 , 0
9646.004  0.0488       09646.004  0.0488       010247.51  0.0488       0
#XS Ineff= 2 , 0
       0                               0
Bank Sta=9646.004,10247.51
Exp/Cntr=0.3,0.1

Type RM Length L Ch R = 1 ,18916.49,678.771400,678.771400,678.771400
XS GIS Cut Line= 6
710812.575752592770515.946326999710814.886037989770587.137631999
710780.962108307 770725.15852644710788.577189228770752.472008639
710984.095417619770862.759670749711133.835000962770903.992309645
#Sta/Elev= 30
9873.9711947.0639883.0941944.8129893.1721939.0969913.2641932.9319923.2711927.655
9933.2771925.1939943.2831923.6599963.6331916.2479973.8271915.1939984.0221911.879
9994.2171909.69310004.531910.586   100151913.57410025.461919.17710035.921920.693
10046.381920.62110067.31 1921.8610087.671924.48610108.131924.63410123.871925.842
10169.791925.975 10227.21928.92310264.121930.11710296.091933.02210340.971935.759
10373.031938.91210404.141940.97910424.891941.77510456.011944.91610496.291945.974
#Mann= 3 , 0 , 0
9873.971  0.0597       09873.971  0.0597       010496.29  0.0597       0
#XS Ineff= 2 , 0
       0                               0
Bank Sta=9873.971,10496.29
Exp/Cntr=0.3,0.1

Type RM Length L Ch R = 1 ,18237.72,796.823400,796.823400,796.823400
XS GIS Cut Line= 6
710430.710000962770157.464531839710530.536389798770270.311754078
710582.619723171770580.641615182710599.980834275 770845.39855963
710771.421806484771055.902031884711114.303750932771442.186754078
#Sta/Elev= 30
8932.8011940.8939044.9251932.9589220.0381925.6039230.1781923.8619250.4571911.684
9260.597 1909.999321.4361929.3649351.8561930.8019361.9961935.3089382.2751938.863
9462.6321939.3989643.0191934.4359675.8441930.3419740.3291926.446 9779.02 1920.37
9829.764 1924.439869.2981919.793  9955.41918.36310000.591908.03410013.971911.002
10030.721919.16910134.31 1916.5710196.421917.53910226.551923.75610294.761924.796
10334.881932.31610362.121941.53710392.251946.31410407.311952.09110451.461958.806
#Mann= 3 , 0 , 0
8932.801  0.0615       08932.801  0.0615       010451.46  0.0615       0
#XS Ineff= 2 , 0
       09491.083                       0
Bank Sta=8932.801,10451.46
Exp/Cntr=0.3,0.1

Type RM Length L Ch R = 1 ,17440.89,491.864900,491.864900,491.864900
XS GIS Cut Line= 6
710055.275973141770487.325642958710173.627554357 770794.28921321
710238.421536237771031.878415599710361.456209809771161.950503096
710402.915220588771234.251896709710458.992406666771507.490062907
#Sta/Elev= 30
9307.8681952.8329444.7031945.8379605.4661936.0059637.589 1935.039709.6841924.884
9730.2831924.3939792.0781926.2459843.8571926.6269854.3681924.9339874.7761918.621
9887.0991916.6269896.1341916.2899914.7911919.2769957.6021916.513 9966.891911.641
9970.9851908.4089981.9371905.03510011.271903.75310039.481910.50410054.071912.686
10079.291914.414 10114.81914.94110136.881916.27210153.761922.43810179.481925.474
10200.181937.88310302.071941.69810332.521943.72910403.571945.131 10426.41944.218
#Mann= 3 , 0 , 0
9307.868  0.0801       09307.868  0.0801       0 10426.4  0.0801       0
#XS Ineff= 2 , 0
       0                               0
Bank Sta=9307.868,10426.4
Exp/Cntr=0.3,0.1

Type RM Length L Ch R = 1 ,16949.03,860.351400,860.351400,860.351400
XS GIS Cut Line= 6
709884.773812469  770475.8596725709925.923110413 770776.33042038
709932.117130398770883.889664702709933.006211963771046.508642585
709959.789862067771342.360365197709909.876667589771685.242309645
#Sta/Elev= 30
9499.0511952.7449660.1141950.6639700.4241944.9659740.6771944.3259770.866 1939.51
9811.078  1937.69921.2431940.3579931.2431937.7029941.2441932.7149951.2451930.745
9961.2461925.2869981.2471910.1649991.2481904.90910001.251903.83810021.261907.029
10031.261911.25410051.271915.626 10121.61918.04210211.931918.35410252.071917.161
10302.251918.924 10342.41917.39410362.471918.08710382.631916.02810423.05 1906.76
10453.371914.71310493.79 1928.5110574.641948.16910645.371951.84810716.361951.982
#Mann= 3 , 0 , 0
9499.051  0.0581       09499.051  0.0581       010716.36  0.0581       0
#XS Ineff= 2 , 0
       0                               0
Bank Sta=9499.051,10716.36
Exp/Cntr=0.3,0.1

Type RM Length L Ch R = 1 ,16088.68,615.243300,615.243300,615.243300
XS GIS Cut Line= 4
709801.369723141770595.832587406709764.477362037770917.013142973
709650.030372143771255.000000015 709308.74819535771657.030504063
#Sta/Elev= 30
  9136.61950.9479196.1561947.7939347.1431943.5789387.4061938.6849397.4711935.798
9427.6691936.382  9447.81938.7929468.325 1935.359616.1331923.3529732.2681922.994
9795.6151919.416 9816.731922.1579855.4071916.9479908.5511916.7939921.6681915.073
9934.7851910.8759974.1371910.3899994.4771904.69310025.38 1903.7310040.831908.058
10052.841913.45710056.291915.65910071.741931.11910087.191943.16410092.191946.686
10105.311952.43210133.551955.78310275.831965.13810318.971970.12210344.081975.271
#Mann= 3 , 0 , 0
  9136.6  0.0687       0  9136.6  0.0687       010344.08  0.0687       0
#XS Ineff= 2 , 0
       0                               0
Bank Sta=9136.6,10344.08
Exp/Cntr=0.3,0.1

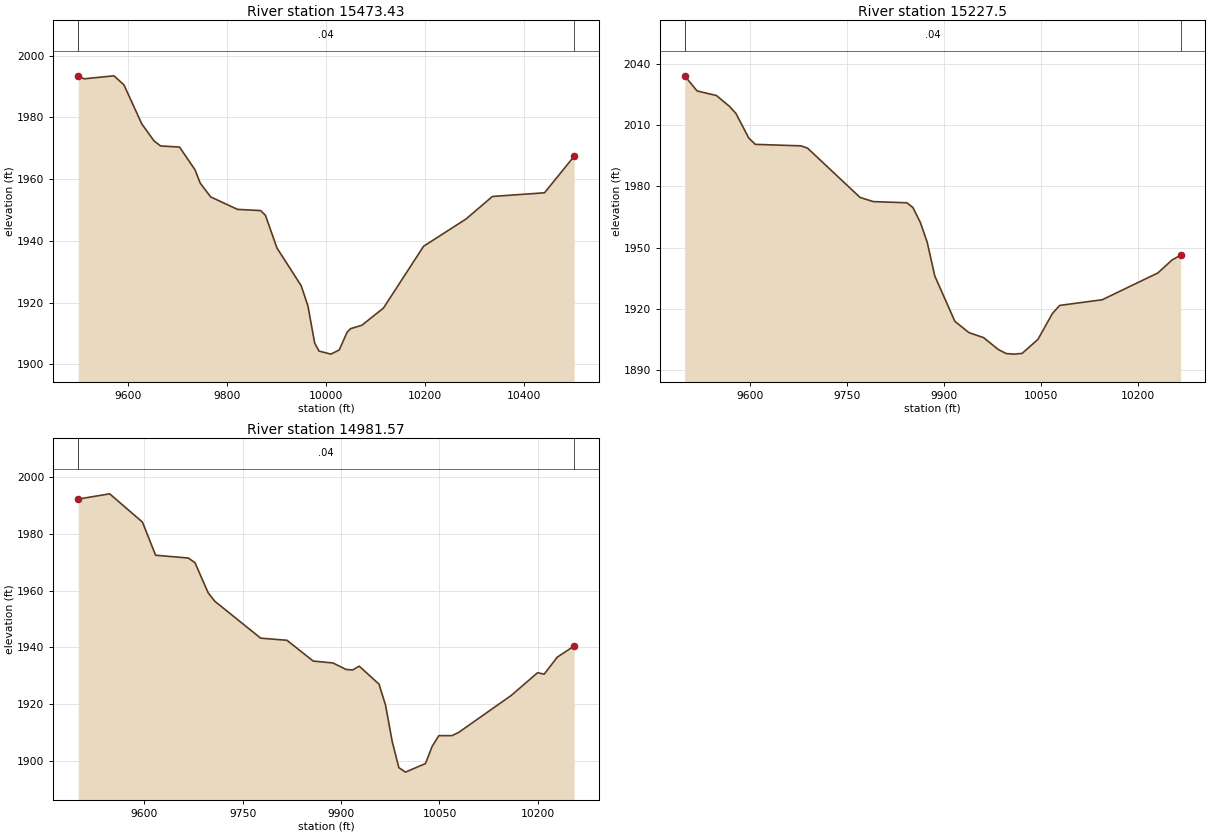
Type RM Length L Ch R = 1 ,15473.43,245.932400,245.932400,245.932400
XS GIS Cut Line= 6
709537.524030419770413.167834637709500.681662014770634.506125611
709426.890607975770797.625053331709379.399912908770857.465472184
709084.684445101 771102.63079474709022.871669083771221.959218934
#Sta/Elev= 30
9499.1371993.3399511.0171992.4769571.267 1993.449591.4881990.5289627.5811977.867
9652.3951972.3499665.5861970.7289703.7861970.3759735.0181963.0329745.5441958.719
9766.6651954.2349820.8071950.1969867.6261949.8029877.3641948.267 9900.521937.713
9949.5841925.4619963.1731918.9359976.762  1906.99985.6311904.29910009.521903.315
10026.451904.67610042.081910.34410048.951911.53310072.251912.67610115.731918.236
10196.721938.23710282.281947.04510335.831954.36910441.131955.56510500.921967.402
#Mann= 3 , 0 , 0
9499.137    0.04       09499.137    0.04       010500.92    0.04       0
#XS Ineff= 2 , 0
       0                               0
Bank Sta=9499.137,10500.92
Exp/Cntr=0.3,0.1

Type RM Length L Ch R = 1 , 15227.5,245.932500,245.932500,245.932500
XS GIS Cut Line= 6
709266.892609021770265.868737816709253.306785508770439.603806563
709204.448118814770648.097450659709182.062851438770702.665154877
709100.469153073770838.900312533709041.255620718770987.746996627
#Sta/Elev= 30
 9499.122034.0699518.2762026.6869548.3162024.4289568.3422019.1419578.355 2015.68
9598.3972003.5879608.4592000.5429678.939 1999.819689.0891998.7299770.4521974.564
 9791.011972.5399842.8021971.9679852.1671969.6379863.7351962.2849874.2021952.752
9886.0411936.1369916.9881913.9989938.6061908.4869961.4241906.0049984.1891900.198
9996.5381898.19410008.851897.92410021.061898.27410045.471905.11310067.951917.802
10079.191921.75810144.941924.51110231.151937.65510252.661943.89210266.241946.337
#Mann= 3 , 0 , 0
 9499.12    0.04       0 9499.12    0.04       010266.24    0.04       0
#XS Ineff= 2 , 0
       0                               0
Bank Sta=9499.12,10266.24
Exp/Cntr=0.3,0.1

Type RM Length L Ch R = 1 ,14981.57,491.864900,491.864900,491.864900
XS GIS Cut Line= 6
708926.388901416770237.011173307708925.753795762770361.640782816
708911.717036527770621.866561214708918.787132742770708.513624384
708939.797563684 770841.61505911708948.592599436770990.651083851
#Sta/Elev= 30
9499.0441992.2219547.0391994.0659597.0481984.1139617.0521972.4569667.1361971.464
9677.1551969.8129697.1931959.2569707.2121956.2869777.3461943.2699817.423 1942.52
9857.4721935.2049887.4771934.5439907.4971932.2599917.5071932.0629927.5381933.408
9957.7261927.1259967.7891919.6719977.9041906.9059988.0481897.6919998.1911896.117
10028.671899.13810038.83 1905.1810048.981908.93910069.161908.97410079.251910.089
10159.581923.12810199.65 1931.1110209.671930.591 10229.71936.593 10255.41940.494
#Mann= 3 , 0 , 0
9499.044    0.04       09499.044    0.04       0 10255.4    0.04       0
#XS Ineff= 2 , 0
       0                               0
Bank Sta=9499.044,10255.4
Exp/Cntr=0.3,0.1