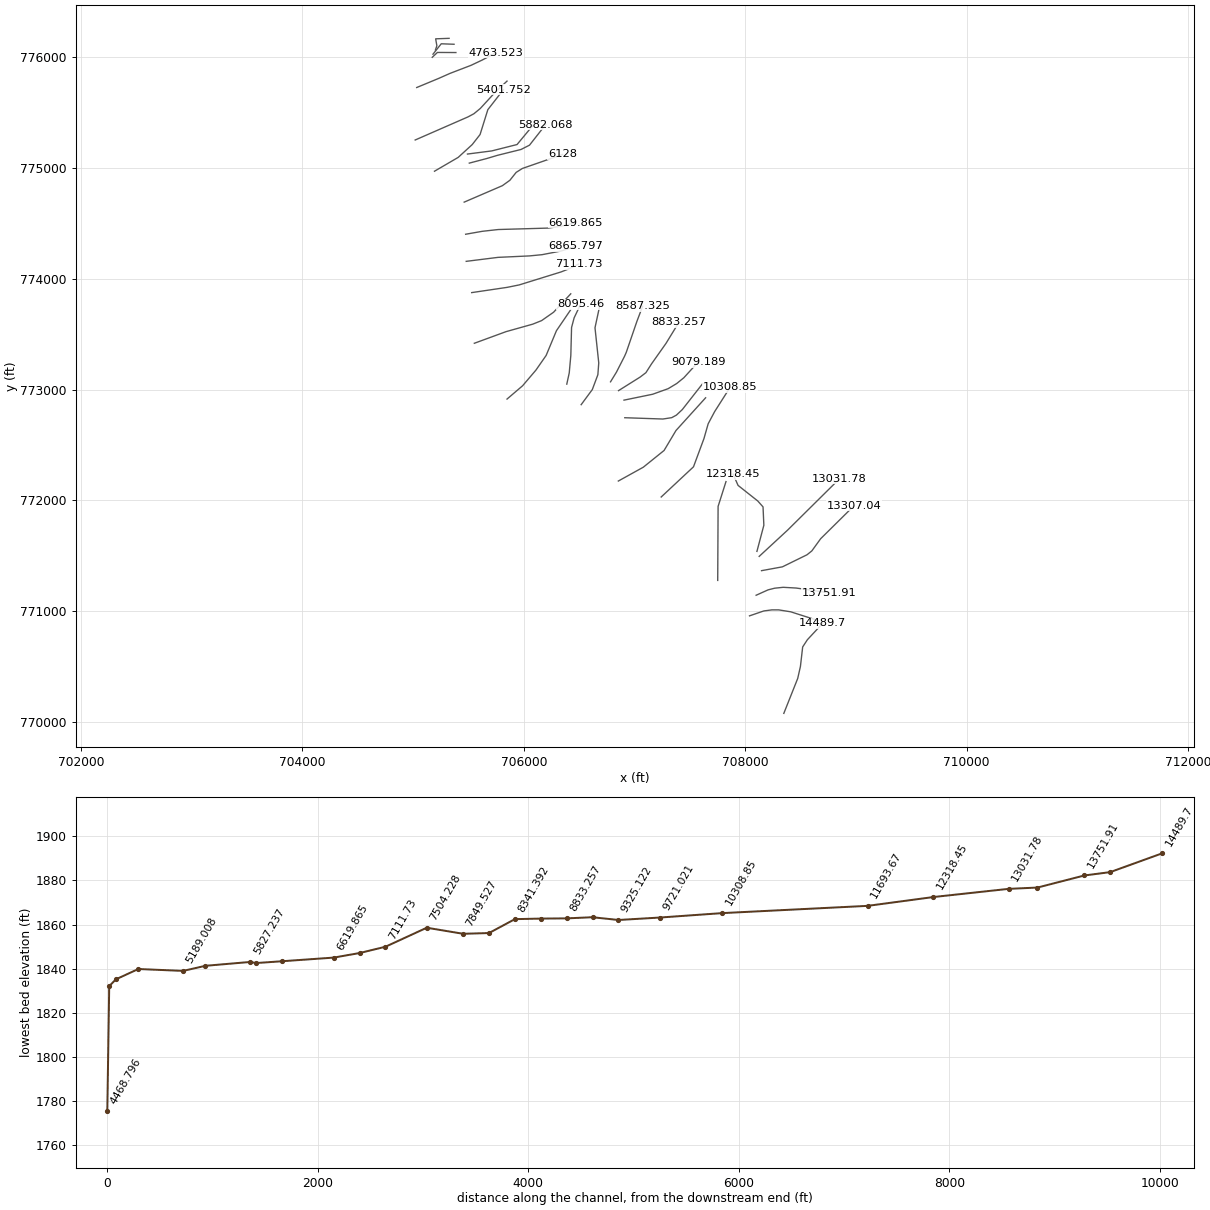
HEC-RAS study 14492_ras.prj: 14492

--- 14492_ras.g01 (geometry) --- (continued)

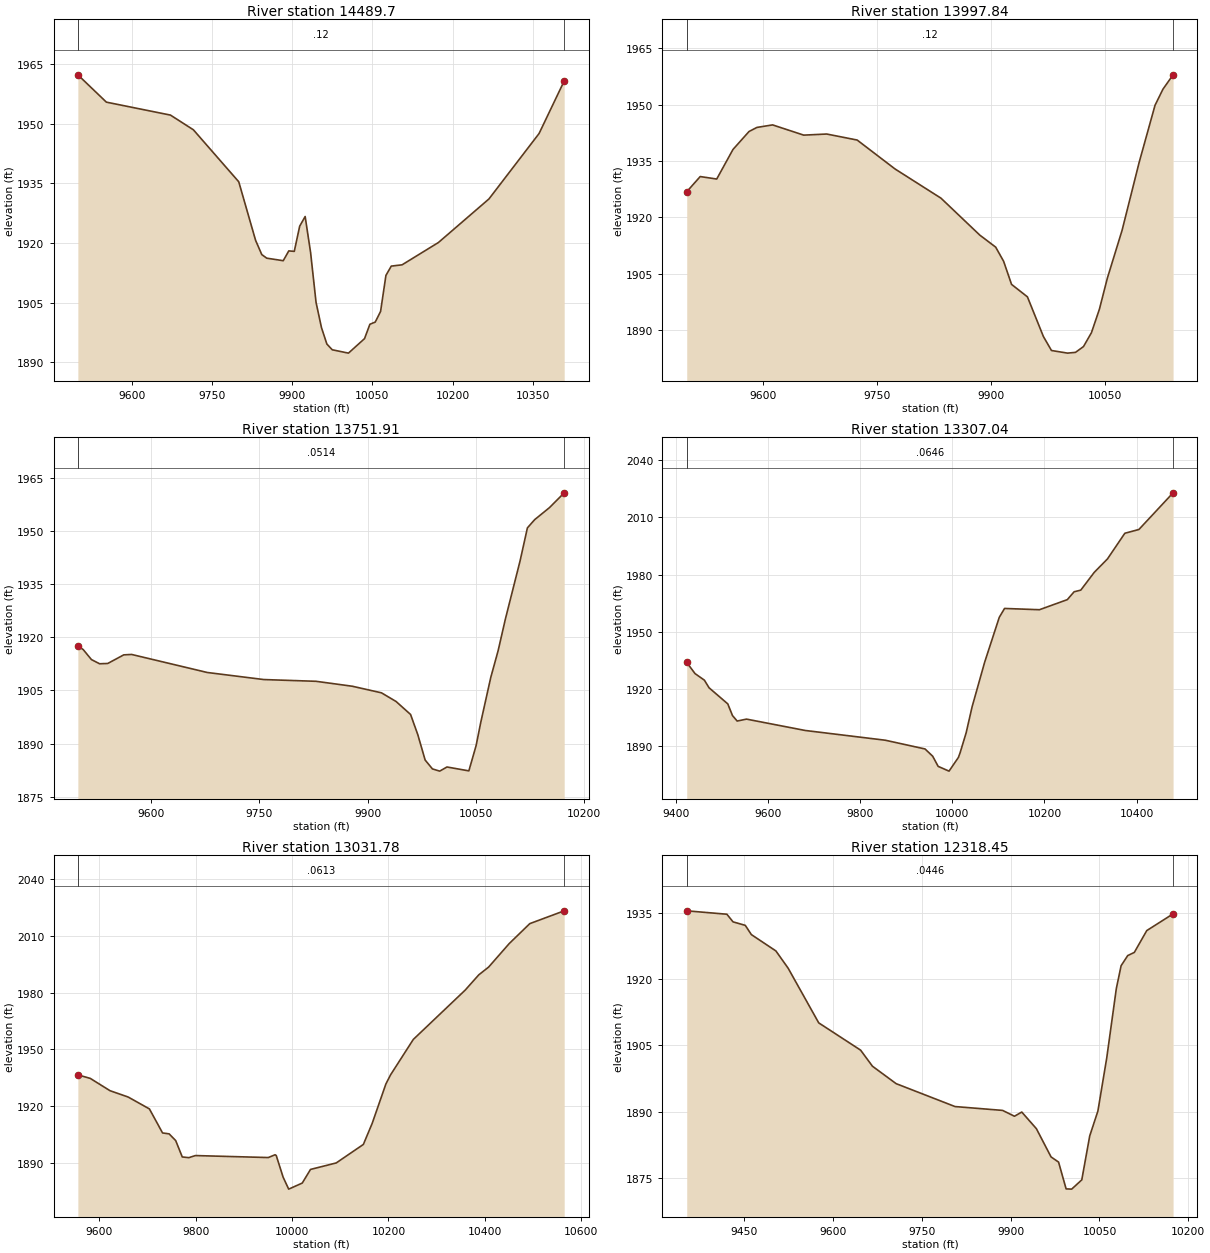
Type RM Length L Ch R = 1 , 14489.7,491.864900,491.864900,491.864900
XS GIS Cut Line= 6
708348.474864577770076.480978305708473.917086069770391.868919042
708498.439878691770500.268648383708518.727488661770676.435641473
708561.108508185770741.381620678708699.445341463770889.837787085
#Sta/Elev= 30
9499.0421962.3539552.3971955.474 9672.33 1952.219715.1621948.5139800.0431935.419
9831.5631920.6629843.1271917.0859852.3391916.1859883.2651915.5479893.6411918.016
9903.8971917.8959914.0761924.2589924.2551926.6719934.4341917.6099944.6131905.067
9954.755 1898.719964.8571894.5689974.9591893.11310005.261892.27210035.341895.922
10045.341899.53610055.341900.08910065.351902.76410075.351911.83910085.351914.184
10105.551914.50510173.581920.12710268.081931.09710361.881947.57910408.861960.805
#Mann= 3 , 0 , 0
9499.042    0.12       09499.042    0.12       010408.86    0.12       0
#XS Ineff= 2 , 0
       0                               0
Bank Sta=9499.042,10408.86
Exp/Cntr=0.3,0.1

Type RM Length L Ch R = 1 ,13997.84,245.932400,245.932400,245.932400
XS GIS Cut Line= 6
708038.694111705770957.183531716708167.683896065771001.503923371
708240.998570859771011.319994926708301.756870389771011.266394645
708410.395933717770993.855149254708657.706528693770914.843004078
#Sta/Elev= 30
9499.1441926.8029516.9031930.8579538.6851930.1969560.1521938.0889581.3011942.868
9591.6491943.9529612.3471944.6319653.4251941.9019683.6891942.1959723.8381940.594
9773.8561932.8729834.4111925.0869885.5641915.2469906.4931912.0439916.9581908.271
9927.4231902.1059948.3521898.787 9969.441888.199 9980.06 1884.48 10001.3 1883.78
10011.781883.98910022.261885.52410032.751889.22410043.231895.46710053.711903.739
10073.151916.51610095.641934.608 10116.61949.85710127.081954.162 10140.4 1957.98
#Mann= 3 , 0 , 0
9499.144    0.12       09499.144    0.12       0 10140.4    0.12       0
#XS Ineff= 2 , 0
       0                               0
Bank Sta=9499.144,10140.4
Exp/Cntr=0.3,0.1

Type RM Length L Ch R = 1 ,13751.91,444.865700,444.865700,444.865700
XS GIS Cut Line= 6
708098.390412648771143.333737785708206.256199154771191.949066794
708266.121629183771207.054688361708342.839714532771215.034508405
708459.096860341771208.522521387708755.323649152771166.487812845
#Sta/Elev= 30
9499.055 1917.599506.5261916.522 9517.831913.7229529.1341912.5359540.4371912.622
9562.5481915.0439573.4551915.1659678.1961910.0769756.5291908.0819828.757 1907.59
    98791906.1969919.317 1904.349939.4761901.9099959.6341898.2359969.7141892.491
9979.7931885.3849989.8721882.8829999.9531882.25710010.041883.426 10040.31882.327
10050.381889.48210056.771895.99210070.661908.699 10080.81916.20910090.941925.206
10111.221941.56110121.361950.865 10131.51953.19710151.771956.54810172.291960.746
#Mann= 3 , 0 , 0
9499.055  0.0514       09499.055  0.0514       010172.29  0.0514       0
#XS Ineff= 2 , 0
       0                               0
Bank Sta=9499.055,10172.29
Exp/Cntr=0.3,0.1

Type RM Length L Ch R = 1 ,13307.04,275.260500,275.260500,275.260500
XS GIS Cut Line= 6
708147.289862047771365.363837411708335.782876949771399.916502138
708557.618389193771508.710226482708601.480600955 771543.77015563
 708681.12333458771653.869254748708982.934740207771952.098885501
#Sta/Elev= 30
9423.013 1933.879441.0191928.0189461.3521924.5539471.5181920.5539512.1851912.095
9522.3521905.9819532.5181903.0899552.8511904.0979680.2791898.1359854.2141893.012
9940.5281888.4279957.2321884.5959969.0821879.2729992.6641876.78110013.041883.972
10016.891886.55910029.831896.89210042.761910.55710070.081934.024 10101.81957.565
10113.281962.22610189.011961.556 10249.61966.86210264.261970.97710278.821971.846
10307.96 1981.1610336.791988.24910374.452001.71210405.092003.70610479.252022.956
#Mann= 3 , 0 , 0
9423.013  0.0646       09423.013  0.0646       010479.25  0.0646       0
#XS Ineff= 2 , 0
       0                               0
Bank Sta=9423.013,10479.25
Exp/Cntr=0.3,0.1

Type RM Length L Ch R = 1 ,13031.78,713.331900,713.331900,713.331900
XS GIS Cut Line= 3
708126.022500932771494.270087406708384.269028723771732.985365197
708850.848889798772195.224948525
#Sta/Elev= 30
9555.9111936.5999581.7541934.7019622.6081928.2069660.1111924.8799704.3151918.581
9731.5511905.8749745.1691905.3969758.7871901.8419772.4041893.1959786.0221892.815
 9799.641893.9269950.8461892.8779964.9231894.3649967.2851893.9489981.4931882.536
9993.0761876.18710021.231879.39210038.331886.59710091.61 1890.0210147.921899.805
10166.21 1910.9410194.621931.75410204.221936.54710251.461955.29810359.061981.377
10387.22 1989.4310407.751993.57410450.382005.97310493.012016.50810564.37 2023.28
#Mann= 3 , 0 , 0
9555.911  0.0613       09555.911  0.0613       010564.37  0.0613       0
#XS Ineff= 2 , 0
       0                               0
Bank Sta=9555.911,10564.37
Exp/Cntr=0.3,0.1

Type RM Length L Ch R = 1 ,12318.45,624.773900,624.773900,624.773900
XS GIS Cut Line= 6
 708105.62319538771539.408976287 708168.12319538771775.520087406
708160.756027669771941.345827281 708113.38197425771994.428827584
707935.193758219772135.444419175707890.345417619772237.325642973
#Sta/Elev= 30
9352.6391935.3949420.4891934.6259430.8331932.9029451.5221932.1119461.8661930.019
9503.2441926.3339523.9331922.4369575.6551910.065 9646.411903.898 9666.431900.263
 9706.471896.3229805.9191891.1479886.3161890.2779906.3531888.9579918.7051889.903
 9943.411886.1429968.1891879.7599980.8631878.5959993.6241872.53610003.01 1872.48
 10020.11874.57610033.521884.51110047.331890.136 10062.21902.08110078.481917.841
10086.551922.98910097.741925.27910108.881925.99410129.881930.92810174.341934.705
#Mann= 3 , 0 , 0
9352.639  0.0446       09352.639  0.0446       010174.34  0.0446       0
#XS Ineff= 2 , 0
       0                               0
Bank Sta=9352.639,10174.34
Exp/Cntr=0.3,0.1

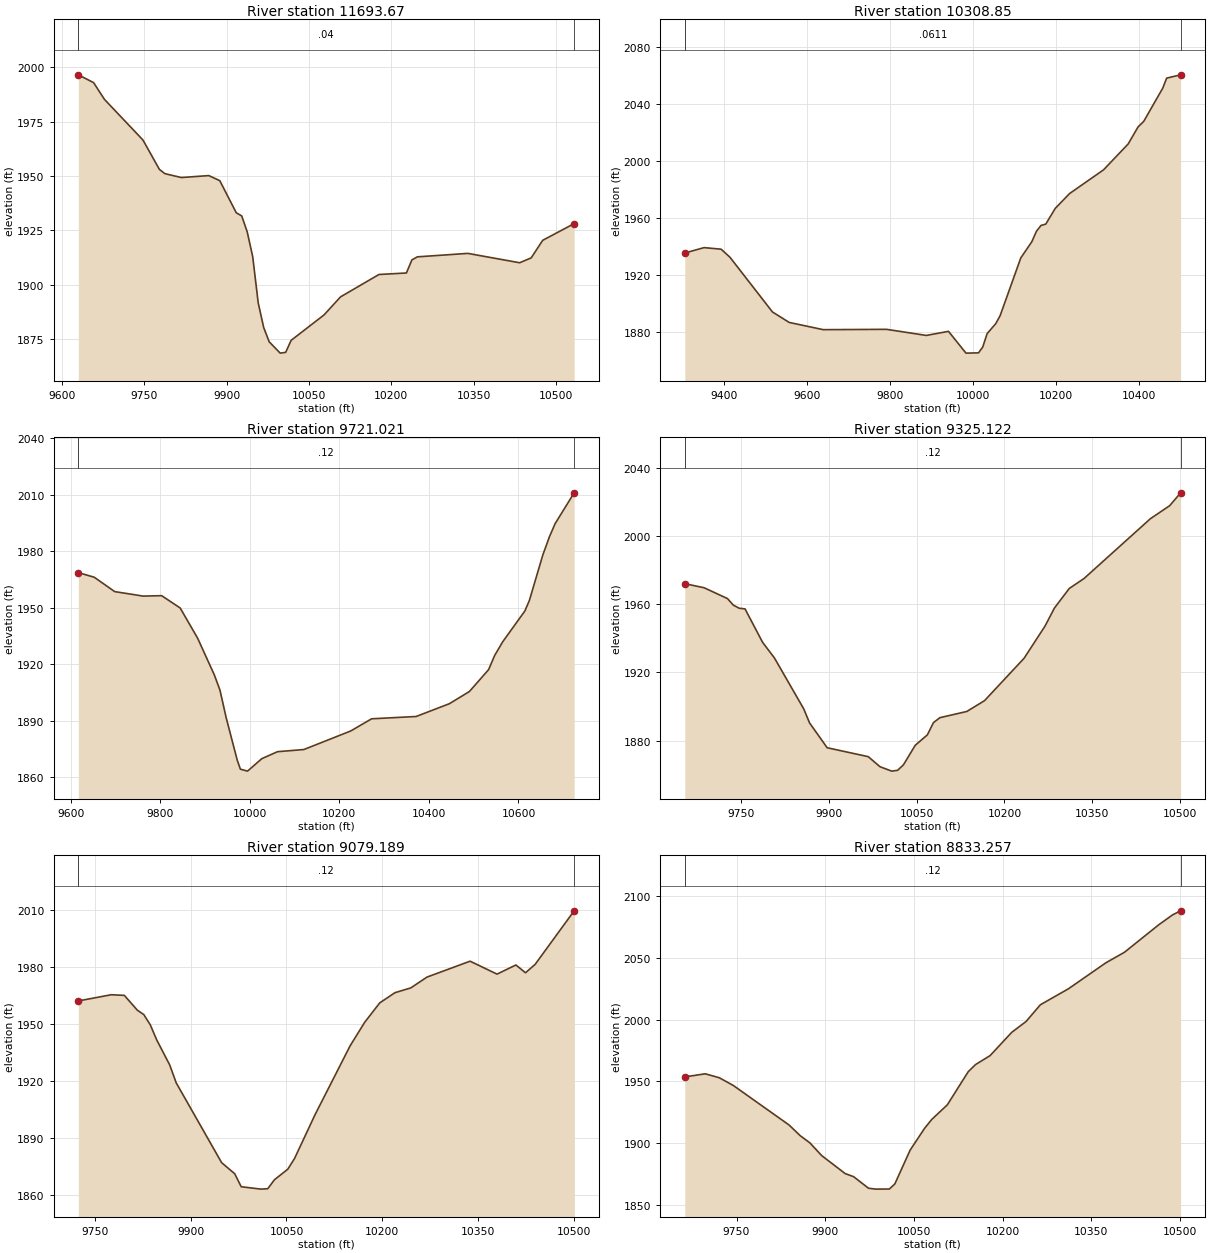
Type RM Length L Ch R = 1 ,11693.67,1384.822400,1384.822400,1384.822400
XS GIS Cut Line= 3
707751.456528723771277.256198511707754.928750962771945.658976302
707826.109306484 772169.61730963
#Sta/Elev= 30
9629.9371996.4729657.6811992.8979677.6811985.1429747.682 1966.499777.6821952.976
9787.6831951.0189817.6831949.2339867.6841950.1329887.6841947.7919917.6841933.048
9927.6841931.5649937.6851924.2069947.6851912.8299957.685 1891.599967.6851880.261
9977.6851873.6989997.685 1868.4810007.691868.82910017.691874.36110077.691886.069
10107.691894.34910177.691904.64410227.691905.33610237.691911.33710247.69 1912.76
10339.631914.34810434.071910.04110455.051912.28510476.041920.36710533.351928.039
#Mann= 3 , 0 , 0
9629.937    0.04       09629.937    0.04       010533.35    0.04       0
#XS Ineff= 2 , 0
       0                               0
Bank Sta=9629.937,10533.35
Exp/Cntr=0.3,0.1

Type RM Length L Ch R = 1 ,10308.85,587.830800,587.830800,587.830800
XS GIS Cut Line= 6
707241.039862067772030.728420734707532.706528723772303.297865182
 707627.04352753772557.807053356 707665.23635721772691.751402478
707723.387509232772801.316362349707863.277049779773021.131409792
#Sta/Elev= 30
9305.5371935.4349352.0181939.2079393.0791938.1179414.3151932.5059516.8361894.081
9557.3231886.7069639.4451881.6459791.9031881.8759887.918 1877.59 9941.26 1880.47
9983.4391865.17910013.711865.36910023.941869.52310034.351878.81610055.161885.854
10065.76 1891.4810115.631932.02110142.221943.37710153.38 1950.7310164.551954.822
10175.741955.68810198.681966.74410233.091977.12110315.021993.77610374.552011.972
10398.362023.92410411.962027.80210457.892051.15210467.232058.14610500.912060.457
#Mann= 3 , 0 , 0
9305.537  0.0611       09305.537  0.0611       010500.91  0.0611       0
#XS Ineff= 2 , 0
       0                               0
Bank Sta=9305.537,10500.91
Exp/Cntr=0.3,0.1

Type RM Length L Ch R = 1 ,9721.021,395.899000,395.899000,395.899000
XS GIS Cut Line= 5
706853.887084275772174.825642973707079.581528693772299.825642958
707267.081528723 772450.86730963707374.720417589772631.422865197
707642.081528723772926.561754063
#Sta/Elev= 30
9617.1041968.572 9652.671966.1039698.3951958.4769761.943  1956.19803.2221956.321
9844.5021949.795 9883.351933.8339920.5831914.4059933.4241906.1519947.112 1891.67
9971.9471869.0189978.9941864.2269994.9341863.18510026.821869.80110061.831873.495
10120.681874.64610225.461884.50510272.031890.96310371.381892.18710445.651898.971
10490.341905.437 10533.31917.07710546.791924.58110564.811931.87110614.261948.201
10624.391953.85210654.181977.81410669.081987.58410681.721994.53110724.31 2010.92
#Mann= 3 , 0 , 0
9617.104    0.12       09617.104    0.12       010724.31    0.12       0
#XS Ineff= 2 , 0
       0                               0
Bank Sta=9617.104,10724.31
Exp/Cntr=0.3,0.1

Type RM Length L Ch R = 1 ,9325.122,245.932500,245.932500,245.932500
XS GIS Cut Line= 6
706912.187786949772746.620092545 707256.48756406772734.907290366
707336.099415326  772747.2163744707378.348124652772770.146641964
 707431.06093014 772819.46960785707616.415658022773055.909650775
#Sta/Elev= 30
9654.1921971.9329687.0731969.5579727.0781963.2069737.0781959.3659747.0781957.537
9757.0791957.1439787.0941937.5289807.1341928.4669857.2351898.5999867.2551890.318
9897.3161875.7679967.457 1870.559987.4981864.66510007.531862.06710017.561862.538
10027.581865.76910047.731877.23610068.321883.28310078.78 1890.4810089.741893.392
10135.81 1897.0410166.031903.37910233.481928.17610269.491947.17510285.321957.624
 10310.71969.108 10335.91974.95110449.322010.02610482.11 2017.6210500.872025.181
#Mann= 3 , 0 , 0
9654.192    0.12       09654.192    0.12       010500.87    0.12       0
#XS Ineff= 2 , 0
       0                               0
Bank Sta=9654.192,10500.87
Exp/Cntr=0.3,0.1

Type RM Length L Ch R = 1 ,9079.189,245.932400,245.932400,245.932400
XS GIS Cut Line= 6
706905.051747123772905.412465691707164.020763046772958.700684221
707304.191453638773009.134223455707381.153784984 773055.48164189
707445.502278857773107.695423214707573.927478147773248.255796769
#Sta/Elev= 30
9723.8021962.2199775.399 1965.489795.9131965.1469816.235 1957.389826.395 1955.05
9836.5561949.6889846.7161941.7099867.038 1928.589877.1981919.1779948.3871877.238
9968.8591871.4339979.0951864.57810010.181863.32310020.671863.53410031.161868.247
10052.131873.81510062.611879.38310094.871902.48610149.811938.65510172.581950.978
 10196.2  1961.210220.071966.56110244.811969.05810270.111974.72910337.771983.109
10380.011976.31310409.631981.11310424.671977.02710439.721981.418 10500.92009.573
#Mann= 3 , 0 , 0
9723.802    0.12       09723.802    0.12       0 10500.9    0.12       0
#XS Ineff= 2 , 0
       0                               0
Bank Sta=9723.802,10500.9
Exp/Cntr=0.3,0.1

Type RM Length L Ch R = 1 ,8833.257,245.932500,245.932500,245.932500
XS GIS Cut Line= 6
706855.695238027772991.360869494707051.712534134773114.358090055
707102.938928664773153.508316328707154.508126447773234.118566595
707283.899443991773417.268024012707400.112618525773606.747030623
#Sta/Elev= 30
9662.5491953.6899697.1451956.1859720.7561953.0169744.653 1946.729838.8131914.763
9857.5391906.149 9874.231900.199 9893.961889.9899933.7981875.3839947.9751872.903
9973.2071863.5299985.5711862.801 10008.51862.88810017.75 1867.0310043.571894.363
10067.831911.91410080.161919.23510106.541931.096 10141.81957.86310154.13 1963.63
10178.791970.91910215.411989.77210239.621998.53610263.832012.08910311.482025.084
10374.372046.00810405.942054.57910464.072076.88410487.322084.85210500.982088.155
#Mann= 3 , 0 , 0
9662.549    0.12       09662.549    0.12       010500.98    0.12       0
#XS Ineff= 2 , 0
       0                               0
Bank Sta=9662.549,10500.98
Exp/Cntr=0.3,0.1

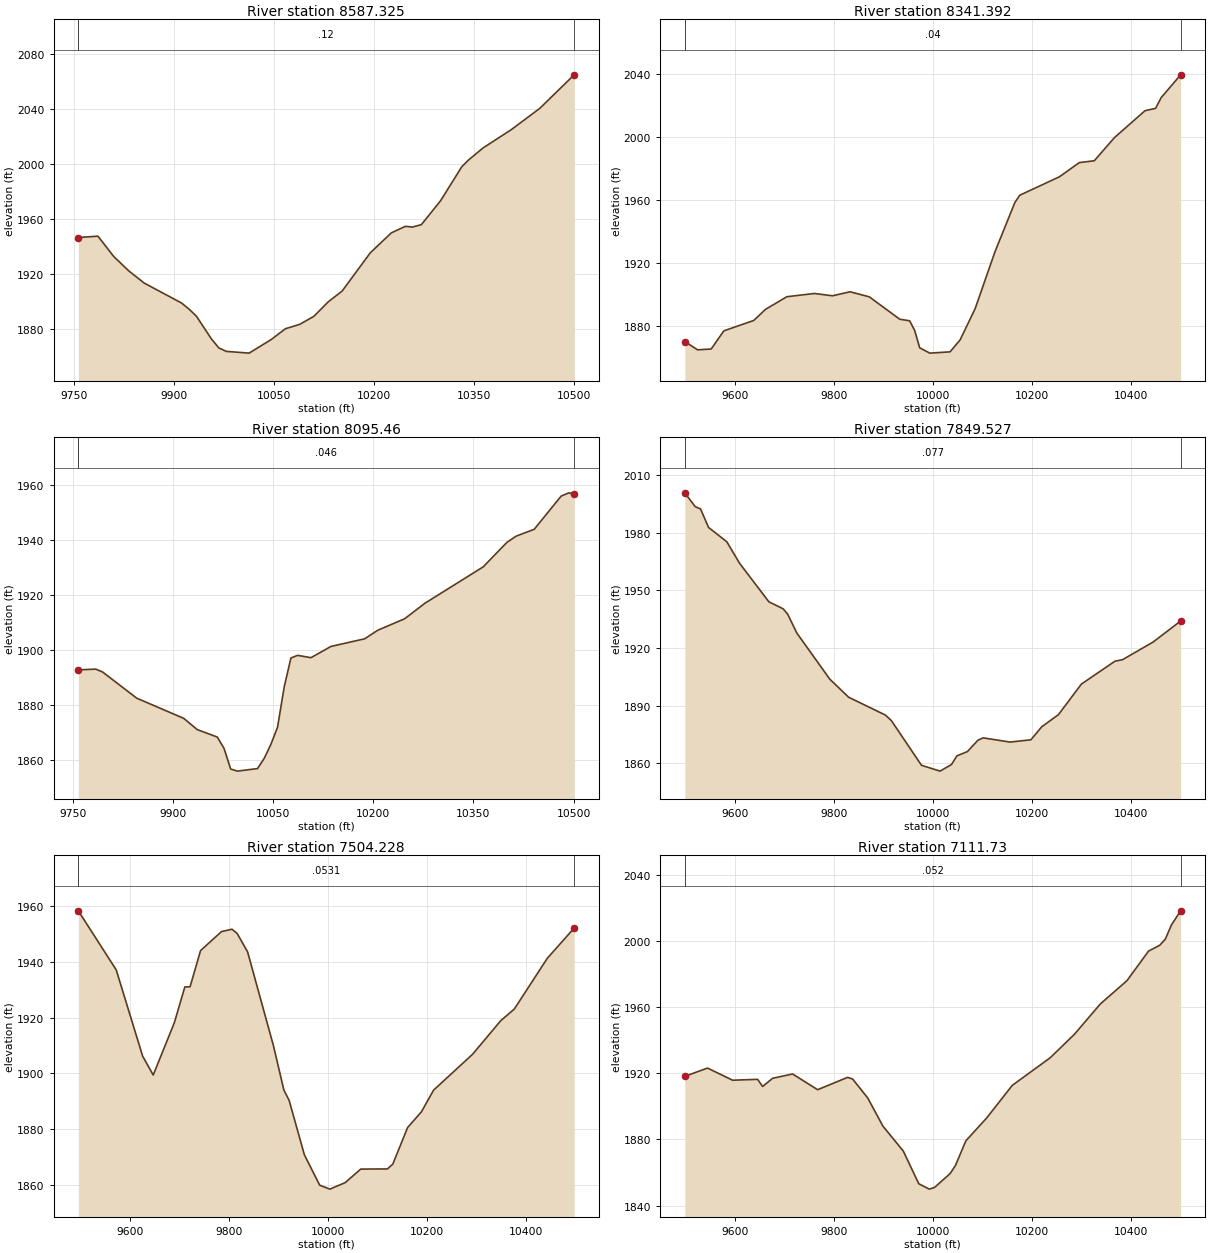
Type RM Length L Ch R = 1 ,8587.325,245.932400,245.932400,245.932400
XS GIS Cut Line= 6
706783.351744662773070.723331813706836.526625819773157.643419828
706909.656675567773300.839968886706925.469491775773336.796668122
707022.219376604773618.516879306 707073.34634343773753.018035703
#Sta/Elev= 30
9757.1121946.6139786.5321947.5989810.1441932.8889833.1451922.2539856.0681913.512
9912.0191899.0579923.1941894.6559934.3691889.4629956.7191873.0699967.8941866.478
9979.247 1863.97 10013.31862.703 10046.31872.51110067.921880.43810089.221883.575
10110.511889.42410131.791899.82410152.891907.75910195.091935.49410226.751950.015
10247.851954.742 10258.41954.21910271.741955.94610300.611973.32810332.261997.901
10342.812003.01810364.012011.531 10406.82024.96910449.332040.33510500.962064.701
#Mann= 3 , 0 , 0
9757.112    0.12       09757.112    0.12       010500.96    0.12       0
#XS Ineff= 2 , 0
       0                               0
Bank Sta=9757.112,10500.96
Exp/Cntr=0.3,0.1

Type RM Length L Ch R = 1 ,8341.392,245.932500,245.932500,245.932500
XS GIS Cut Line= 6
706518.164566545772864.461302171706618.926436801773001.026667588
706669.068634304773135.090373617706677.087936383773241.750296197
706643.134714408773559.046415274706697.779823052773812.924558849
#Sta/Elev= 30
9499.1681869.7699525.1021864.5459552.4621865.0759578.0991876.6349638.4641883.222
9662.1061890.2599705.2731898.3219760.8741900.3989797.588 1898.939833.0231901.474
9871.8661898.2679933.3851884.0329953.5071883.0029963.5681876.8929973.7431865.843
9994.1471862.45110035.011863.26710055.33 1870.8310085.651890.64410125.891926.985
   101661958.265   101761962.91310256.081974.63110296.261983.65410326.491984.816
10367.211999.56710429.062016.68610450.212018.12210461.53 2024.9610500.882039.483
#Mann= 3 , 0 , 0
9499.168    0.04       09499.168    0.04       010500.88    0.04       0
#XS Ineff= 2 , 0
       0  9896.1                       0
Bank Sta=9499.168,10500.88
Exp/Cntr=0.3,0.1

Type RM Length L Ch R = 1 , 8095.46,245.932400,245.932400,245.932400
XS GIS Cut Line= 6
706388.306145721773049.920963782706410.475382453773150.875736414
706424.876445937773309.949903831706431.494358706773561.274677895
706454.636974679773648.399242338706513.292862394773772.133508306
#Sta/Elev= 30
9758.5421892.8859784.7611893.1579795.0291892.0919845.9851882.6149916.398 1875.29
9936.4751871.2299966.5911868.502 9976.631864.4369986.6681856.9029996.7071856.142
10026.851857.06210036.851860.77810046.851865.84210056.851872.11710066.861886.789
10076.861897.19710086.861898.15510106.861897.31410136.871901.39610187.191904.152
10206.911907.273 10247.11911.42810277.421917.05310364.811930.27310400.111939.125
10414.191941.42210441.121943.89510481.471955.95210492.821957.13110500.921956.661
#Mann= 3 , 0 , 0
9758.542   0.046       09758.542   0.046       010500.92   0.046       0
#XS Ineff= 2 , 0
       0                               0
Bank Sta=9758.542,10500.92
Exp/Cntr=0.3,0.1

Type RM Length L Ch R = 1 ,7849.527,345.299000,345.299000,345.299000
XS GIS Cut Line= 6
705848.639837375772915.109605356705989.324626293773035.303948043
706109.638044584773176.559007363706201.843612282773309.020084239
706294.738220222773532.220274899706422.508867242773720.099591459
#Sta/Elev= 30
9499.0792000.9279519.994 1993.769531.0051992.4789547.0561982.8819583.9151975.433
 9609.631964.2449668.9431944.107 9697.721940.4679706.7531937.7559725.5641927.773
 9792.031903.7819830.0171894.3659904.3441885.0529916.4281882.1889977.3521858.856
10014.841855.81210037.971859.286 10048.91863.75910070.251866.018 10091.41871.942
10101.981873.16110156.261870.96110198.351872.14310220.361878.94710254.121885.283
10300.451901.20710368.091913.09610383.821913.95710445.391923.13110500.921934.081
#Mann= 3 , 0 , 0
9499.079   0.077       09499.079   0.077       010500.92   0.077       0
#XS Ineff= 2 , 0
       0                               0
Bank Sta=9499.079,10500.92
Exp/Cntr=0.3,0.1

Type RM Length L Ch R = 1 ,7504.228,392.498400,392.498400,392.498400
XS GIS Cut Line= 6
705553.345164675773419.005879674705840.018594844 773524.12628409
706081.147005572773591.733366412706160.848722119773623.669151079
706269.279143648773699.578004271706424.258611117773865.682019592
#Sta/Elev= 30
9496.1681958.2059572.7181937.0569626.1341906.169  9647.51899.4149690.145 1918.13
9711.3561930.9489721.9621931.0219743.1731943.9789785.5941950.7879806.7421951.621
9817.2221950.063 9838.18 1943.519890.5771909.7969911.536 1893.989922.015 1890.39
9952.9611870.8329983.8651859.96710004.461858.55810035.411860.88610066.74 1865.73
10120.621865.78810131.591867.50810161.471880.59510189.351886.23310213.971893.998
10292.741906.84210349.751918.88210377.141923.04810443.791941.21610498.011952.032
#Mann= 3 , 0 , 0
9496.168  0.0531       09496.168  0.0531       010498.01  0.0531       0
#XS Ineff= 2 , 0
       0                               0
Bank Sta=9496.168,10498.01
Exp/Cntr=0.3,0.1

Type RM Length L Ch R = 1 , 7111.73,245.932500,245.932500,245.932500
XS GIS Cut Line= 6
705529.571052564773876.571282552705849.868518598773924.026446699
705958.567155201773946.033801647706337.728409764774063.616520431
706402.142402841774089.095690589706492.650665049774133.438046603
#Sta/Elev= 30
9499.0231918.2699545.0271923.2779595.6611915.9179646.1831916.4559656.2851912.122
9676.4881917.0879716.8931919.7029767.4011910.1749828.0391917.6499838.1961916.655
 9868.671905.1599899.2951888.1329940.4861873.0249971.8171853.1999993.0211849.928
10003.63 1850.9410035.341859.39410045.911864.26810067.061879.23710108.841892.965
10160.79 1912.8110237.171929.46610285.921943.60610338.69 1962.1310392.46 1976.22
10436.221994.17210458.62 1997.6510469.862001.301 10482.52010.05110500.952018.555
#Mann= 3 , 0 , 0
9499.023   0.052       09499.023   0.052       010500.95   0.052       0
#XS Ineff= 2 , 0
       0                               0
Bank Sta=9499.023,10500.95
Exp/Cntr=0.3,0.1

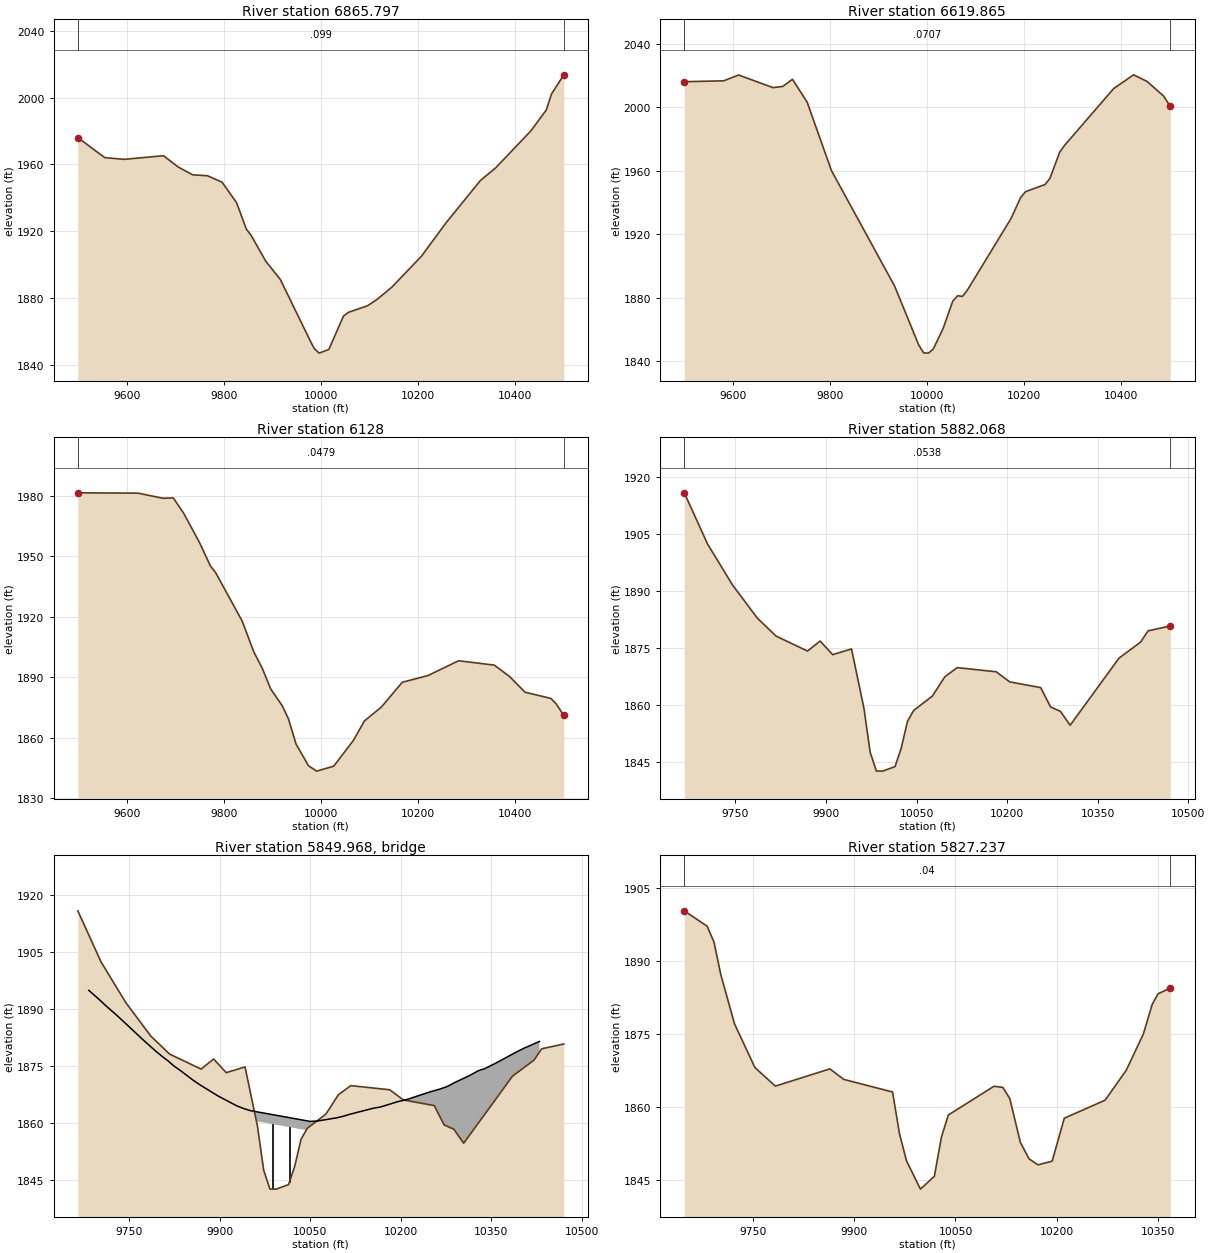
Type RM Length L Ch R = 1 ,6865.797,245.932400,245.932400,245.932400
XS GIS Cut Line= 6
705480.054956921774158.941725345705767.286807211774194.879090788
706051.170252655774207.997525864706165.026136162774219.105953802
706338.388802571774252.597437293706468.942977585774294.246435015
#Sta/Elev= 30
 9499.031976.0579554.5481964.0639594.9641963.0399675.6511965.2099705.8161958.472
9735.9821953.7579766.1471953.2299796.2871949.4079826.3521937.1189846.3961921.322
9856.4181917.5049886.4831902.0929916.5431891.1329979.8771853.4379986.5711849.793
9996.5751847.07610016.591849.297 10046.61869.20810056.611871.44410096.691875.492
10116.75  1879.410146.911886.67410207.441905.07710258.091925.03110328.981950.378
10360.381957.92310433.211980.11510464.921992.60710475.532002.08410500.952013.612
#Mann= 3 , 0 , 0
 9499.03   0.099       0 9499.03   0.099       010500.95   0.099       0
#XS Ineff= 2 , 0
       0                               0
Bank Sta=9499.03,10500.95
Exp/Cntr=0.3,0.1

Type RM Length L Ch R = 1 ,6619.865,491.864900,491.864900,491.864900
XS GIS Cut Line= 6
705474.849035111774403.676756788705625.744429182774430.252752222
705769.250561343774446.286248567706221.060071147774459.296778442
706334.917282832774475.456680226706468.089279213774507.799640035
#Sta/Elev= 30
9499.0272016.221 9580.582016.7999610.9952020.4549681.7532012.4999701.9172013.256
 9722.08 2017.759752.2482003.3739802.4371960.1329932.5381887.3669982.5381850.036
9992.5381845.16310002.541845.00810012.541847.71510032.541860.44810052.541877.813
10062.541881.20610072.541880.78610082.54 1884.6910172.581929.88110192.611943.241
10202.641946.87310242.771951.37110252.811955.21310272.951971.73410283.021976.061
10384.422011.93110425.342020.56610452.922016.43610487.382007.15810500.972000.642
#Mann= 3 , 0 , 0
9499.027  0.0707       09499.027  0.0707       010500.97  0.0707       0
#XS Ineff= 2 , 0
       0                               0
Bank Sta=9499.027,10500.97
Exp/Cntr=0.3,0.1

Type RM Length L Ch R = 1 ,    6128,245.932500,245.932500,245.932500
XS GIS Cut Line= 6
705461.811430111774693.794790635705806.601086542774842.287660052
705874.372269259774891.048352247705931.203712411774962.360870524
 705987.20157344774997.774045954706350.178590007775124.139192163
#Sta/Elev= 30
9499.1111981.6359623.3651981.4819674.269 1978.939695.8821979.1049717.4961971.414
9750.2671956.7569772.237 1945.389783.2231941.9649838.0051917.8579861.7511902.668
9879.8971894.1169896.7641884.1599920.5741875.7879933.1471869.427 9948.951856.785
9974.5851846.0249991.379 1843.3510026.57  1845.810067.211858.62910089.781868.261
10124.811875.194 10167.91887.49310220.88 1890.8410284.031898.194 10357.71896.014
10389.281890.32410421.031882.54910474.121879.48710484.741876.92110500.861871.052
#Mann= 3 , 0 , 0
9499.111  0.0479       09499.111  0.0479       010500.86  0.0479       0
#XS Ineff= 2 , 0
       0                               0
Bank Sta=9499.111,10500.86
Exp/Cntr=0.3,0.1

Type RM Length L Ch R = 1 ,5882.068,54.830200,54.830200,54.830200
XS GIS Cut Line= 6
705507.957327545775046.088074535705664.934191585 775087.39777559
705762.949027002775116.593585402705975.276931196775169.436811924
706051.743210644775208.322536901706197.453792602775393.840648964
#Sta/Elev= 30
9665.1911915.8879703.4951902.4619744.8571891.6489786.218 1882.85 9817.241878.126
9869.318 1874.179890.1861876.8289911.0551873.2319942.2021874.7429962.8121859.082
9973.1171847.5029983.4221842.5589993.7271842.52910014.341843.72610024.641848.633
10034.951855.66910045.251858.53710076.171862.30810096.781867.39710117.391869.812
10181.931868.71610204.371866.04710255.581864.54810272.031859.45110288.21  1858.3
 10304.41854.62110385.35 1872.3110420.881876.518 10433.61879.51510470.271880.789
#Mann= 3 , 0 , 0
9665.191  0.0538       09665.191  0.0538       010470.27  0.0538       0
#XS Ineff= 2 , 0
       09928.843         10140.7       0
Bank Sta=9665.191,10470.27
Exp/Cntr=0.3,0.1

Type RM Length L Ch R = 3 ,5849.968,,,
BEGIN DESCRIPTION:
END DESCRIPTION:
Bridge Culvert--1,0,-1,-1, 0
Deck Dist Width WeirC Skew NumUp NumDn MinLoCord MaxHiCord MaxSubmerge Is_Ogee
16.424300,21.981600,2.6,0, 41, 41, , , 0.95, 0, 0,0,,
 9683.32 9700.89 9710.92 9732.38 9772.62 9793.40 9803.79 9814.18 9824.57 9834.96
 9855.75 9866.10 9897.13 9928.16 9938.51 9950.39 9961.40 9961.4010042.1110042.11
10050.0510062.6410093.6810104.0210114.3610154.4610166.6810194.9010210.4510249.69
10262.0610274.9610281.3410287.8710313.6710328.8110339.4810360.4610391.0910404.00
10429.94
 1894.93 1892.47 1890.96 1887.97 1881.98 1879.02 1877.64 1876.39 1874.96 1873.81
 1871.29 1870.16 1867.11 1864.51 1863.85 1863.24 1862.92 1862.92 1860.61 1860.61
 1860.38 1860.49 1861.32 1861.69 1862.20 1863.84 1864.18 1865.57 1866.16 1868.22
 1868.76 1869.44 1869.91 1870.50 1872.44 1873.75 1874.30 1875.98 1878.62 1879.65
 1881.45
  894.93  892.47  890.96  887.97  881.98  879.02  877.64  876.39  874.96  873.81
  871.29  870.16  867.11  864.51  863.85  863.24  862.92 1860.42 1858.11  860.61
  860.38  860.49  861.32  861.69  862.20  863.84  864.18  865.57  866.16  868.22
  868.76  869.44  869.91  870.50  872.44  873.75  874.30  875.98  878.62  879.65
  881.45
 9683.32 9700.89 9710.92 9732.38 9772.62 9793.40 9803.79 9814.18 9824.57 9834.96
 9855.75 9866.10 9897.13 9928.16 9938.51 9950.39 9958.60 9958.6010039.3110039.31
10050.0510062.6410093.6810104.0210114.3610154.4610166.6810194.9010210.4510249.69
10262.0610274.9610281.3410287.8710313.6710328.8110339.4810360.4610391.0910404.00
10429.94
 1894.93 1892.47 1890.96 1887.97 1881.98 1879.02 1877.64 1876.39 1874.96 1873.81
 1871.29 1870.16 1867.11 1864.51 1863.85 1863.24 1863.00 1863.00 1860.69 1860.69
 1860.38 1860.49 1861.32 1861.69 1862.20 1863.84 1864.18 1865.57 1866.16 1868.22
 1868.76 1869.44 1869.91 1870.50 1872.44 1873.75 1874.30 1875.98 1878.62 1879.65
 1881.45
  894.93  892.47  890.96  887.97  881.98  879.02  877.64  876.39  874.96  873.81
  871.29  870.16  867.11  864.51  863.85  863.24  863.00 1860.50 1858.19  860.69
  860.38  860.49  861.32  861.69  862.20  863.84  864.18  865.57  866.16  868.22
  868.76  869.44  869.91  870.50  872.44  873.75  874.30  875.98  878.62  879.65
  881.45
Pier Skew, UpSta & Num, DnSta & Num=  ,9987.80, 2 ,9985.01, 2 , 0 , 0 , 0 ,,
    3.00    3.00
  862.16 1862.16
    3.00    3.00
  862.24 1862.24
Pier Skew, UpSta & Num, DnSta & Num=  ,10015.71, 2 ,10012.91, 2 , 0 , 0 , 0 ,,
    3.00    3.00
  861.36 1861.36
    3.00    3.00
  861.44 1861.44
BR Coef=-1 , 0 , 0 ,, 0 ,,,0.8,0,1,0,
WSPro=,,,, 1 ,,,, 0 ,,,, 0 ,,,,-1 ,-1 ,-1 , 0 , 0 , 0 , 0 , 0
BC Design=,, 0 ,, 0 ,,,,,,

Type RM Length L Ch R = 1 ,5827.237,425.485800,425.485800,425.485800
XS GIS Cut Line= 4
705491.433447093775127.956391186705711.317082554775156.419974282
705939.181665897775213.928654835 706106.57245025775415.622127727
#Sta/Elev= 30
9648.8821900.2949682.7281897.1249692.8121893.8619702.8951887.1669723.0621877.072
9753.3121868.0499783.5631864.227 9864.231867.7749884.7121865.6129956.9071863.013
 9967.221854.4099977.5341848.8649998.1611843.03110018.791845.675 10029.11853.662
10039.421858.285   101071864.195   101201863.97110130.381861.66910145.991852.635
10158.98 1849.2510171.981848.03110193.011848.77910210.961857.621 10271.31861.327
10302.621867.49210327.921874.94310340.921881.018 10349.61883.21810367.721884.393
#Mann= 3 , 0 , 0
9648.882    0.04       09648.882    0.04       010367.72    0.04       0
#XS Ineff= 2 , 0
       09925.912         10107.1       0
Bank Sta=9648.882,10367.72
Exp/Cntr=0.3,0.1

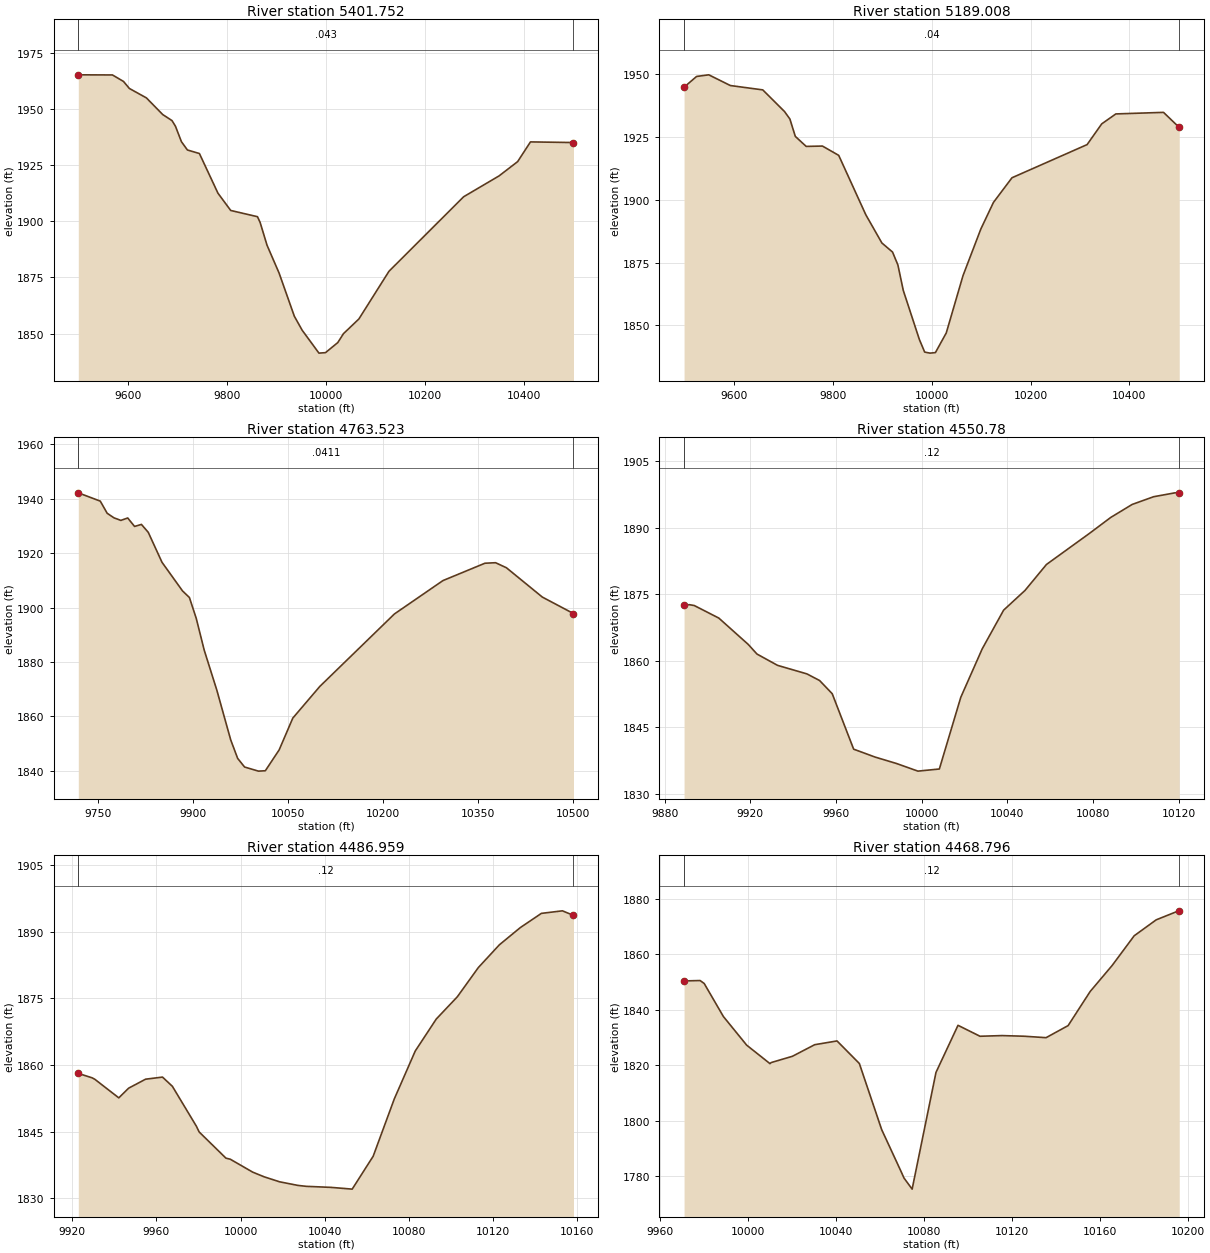
Type RM Length L Ch R = 1 ,5401.752,212.743000,212.743000,212.743000
XS GIS Cut Line= 6
705193.508441301774972.847697576705407.445596828775097.673803924
705534.373829603775213.568958506705605.117644188775304.060135404
705675.361474242775528.854086879705816.017643939775709.329619831
#Sta/Elev= 30
9499.0591965.1599568.1581965.1059590.5341962.2069602.3921959.086 9636.871954.891
9669.7531947.4979688.6481944.7829695.6311942.2699707.6581935.4049719.7921931.706
9744.0611930.1329781.5961912.4659807.3851904.7879861.5321902.0119866.863 1899.47
9880.8431889.3239905.3431876.8719936.0721857.7259951.8271851.517 9985.891841.288
9999.0821841.49910023.911845.96310035.421849.93710066.641856.48410127.521877.715
10278.571910.886 10350.21920.16410387.811926.52410413.771935.30510500.791935.015
#Mann= 3 , 0 , 0
9499.059   0.043       09499.059   0.043       010500.79   0.043       0
#XS Ineff= 2 , 0
       0                               0
Bank Sta=9499.059,10500.79
Exp/Cntr=0.3,0.1

Type RM Length L Ch R = 1 ,5189.008,425.485800,425.485800,425.485800
XS GIS Cut Line= 6
705019.153104848775254.870987111705496.374892035775463.553077268
705549.277049332775491.872948123705607.047831831775539.374363762
705740.954665862775685.208707682705848.580143196775786.861939191
#Sta/Elev= 30
9499.0111944.8269524.3751949.0979549.0181949.7449592.6481945.483 9658.271943.748
9702.1661935.154 9713.141932.1529724.1141925.2369746.0631921.2559778.9851921.393
9811.9071917.6899866.6921894.0699899.1861882.8329920.8491879.1929931.6811874.048
9942.5121863.9589975.0071844.4519985.8381839.386 9996.671838.97510007.531839.186
10029.491847.002 10063.41869.82510099.48 1888.3810125.021898.97510162.491908.775
10314.461921.97210344.041930.22410372.631934.18110469.071934.80210500.921928.791
#Mann= 3 , 0 , 0
9499.011    0.04       09499.011    0.04       010500.92    0.04       0
#XS Ineff= 2 , 0
       0                               0
Bank Sta=9499.011,10500.92
Exp/Cntr=0.3,0.1

Type RM Length L Ch R = 1 ,4763.523,212.742900,212.742900,212.742900
XS GIS Cut Line= 6
705032.911162534 775728.72955551705232.494420106775811.602402498
 705333.72871433775856.432553444705523.501885425775929.187505761
705627.470668579775978.365748248705748.367193907776043.036805506
#Sta/Elev= 30
9718.7511942.1839753.4961939.1279764.3241934.6699775.1521932.979 9785.981932.044
9796.8081932.9329807.6361929.8229818.4631930.5669829.2911927.6469850.9471916.648
 9883.431906.0989894.2581903.6869905.086 1895.999917.6391884.337  9937.6 1869.59
9959.4961851.3259970.4451844.5299981.3931841.342 10003.31839.82910014.211839.971
10036.051847.64610057.591859.33110100.241870.97410218.09 1897.6310294.741909.906
10361.121916.29310377.921916.47710395.071914.61710451.781903.83610500.961897.783
#Mann= 3 , 0 , 0
9718.751  0.0411       09718.751  0.0411       010500.96  0.0411       0
#XS Ineff= 2 , 0
       0                               0
Bank Sta=9718.751,10500.96
Exp/Cntr=0.3,0.1

Type RM Length L Ch R = 1 , 4550.78,63.820900,63.820900,63.820900
XS GIS Cut Line= 3
705173.160521358776001.736517206705219.905597746776045.540618435
705386.977415442776044.745038345
#Sta/Elev= 26
9889.0831872.5469891.6041872.6339893.8561872.4449905.3091869.6199919.013  1863.7
9923.1051861.5269932.7181858.9759946.4221857.0549952.3541855.557 9958.241852.586
 9968.241840.102 9978.241838.326 9988.241836.876 9998.241835.15810008.241835.636
10018.241851.77410028.241862.68210038.241871.40610048.241875.85410058.241881.692
10078.241888.66810088.241892.28210098.241895.20910108.241896.94510118.241897.824
10120.221897.824
#Mann= 3 , 0 , 0
9889.083    0.12       09889.083    0.12       010120.22    0.12       0
#XS Ineff= 2 , 0
       0                               0
Bank Sta=9889.083,10120.22
Exp/Cntr=0.3,0.1

Type RM Length L Ch R = 1 ,4486.959,18.163300,18.163300,18.163300
XS GIS Cut Line= 3
705180.142426133 776029.87857613705254.443125457776123.847107604
705370.264803797776119.476478249
#Sta/Elev= 30
9922.7961858.1129929.3251857.1249930.6281856.7989942.0741852.6079946.7511854.784
9954.8221856.8079962.874 1857.28 9967.571855.2099978.9971846.2259980.3191844.929
9993.0671839.032 9995.121838.79510005.821835.88210011.241834.83510018.561833.714
10027.371832.89310031.31 1832.6910043.151832.45110053.16 1832.0610063.161839.476
10073.171852.33210083.181863.15810093.18 1870.3510103.19 1875.35 10113.21881.931
 10123.21887.05210133.211890.94210143.221894.13510153.231894.70710158.491893.675
#Mann= 3 , 0 , 0
9922.796    0.12       09922.796    0.12       010158.49    0.12       0
#XS Ineff= 2 , 0
       0                               0
Bank Sta=9922.796,10158.49
Exp/Cntr=0.3,0.1

Type RM Length L Ch R = 1 ,4468.796,84.182900,84.182900,84.182900
XS GIS Cut Line= 4
705201.995573014776068.121583134 705215.00000003776105.525381267
705204.180887699776168.646058649705325.465852737776173.016688034
#Sta/Elev= 29
9970.9131850.3949978.1951850.5389980.0621849.4749988.7821837.559 9999.371827.229
10009.961820.56510010.511820.96110020.131823.21310030.271827.40110040.421828.757
10050.561820.61810060.711796.76410069.711781.34210070.851779.30410074.551775.312
10075.371778.52710085.381817.39810095.391834.38910105.391830.443 10115.41830.682
10125.411830.45410135.411829.93510145.421834.28510155.431846.57510165.431855.975
10175.441866.67810185.451872.43210195.451875.61410195.921875.679
#Mann= 3 , 0 , 0
9970.913    0.12       09970.913    0.12       010195.92    0.12       0
#XS Ineff= 2 , 0
       0                10034.96       0
Bank Sta=9970.913,10195.92
Exp/Cntr=0.3,0.1