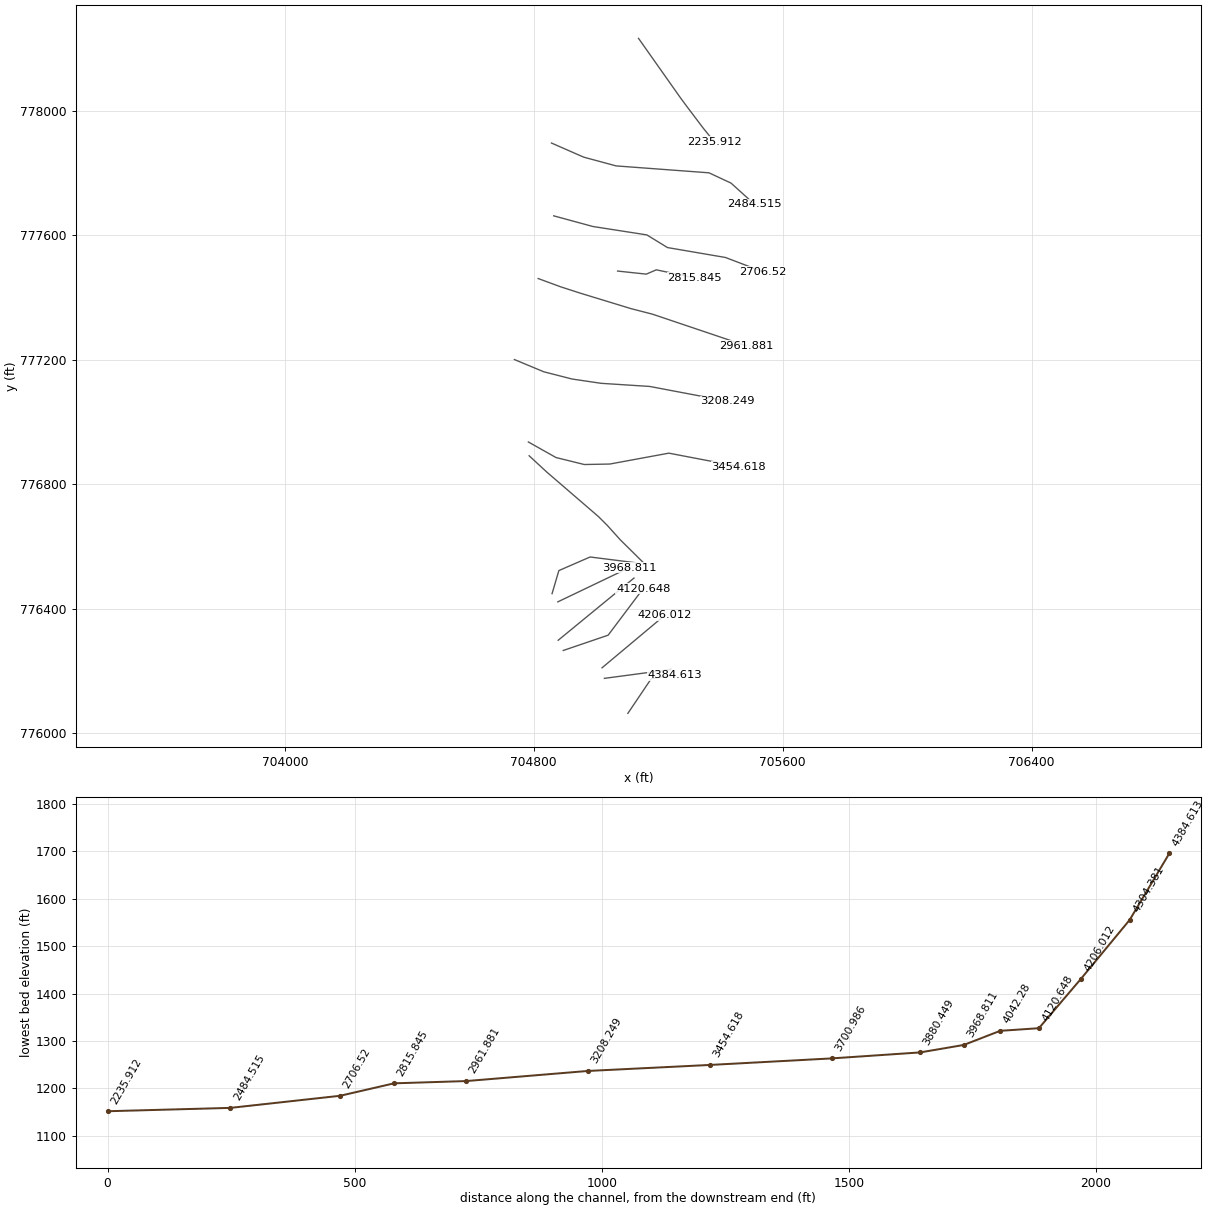
HEC-RAS study 14492_ras.prj: 14492

--- 14492_ras.g01 (geometry) --- (continued)

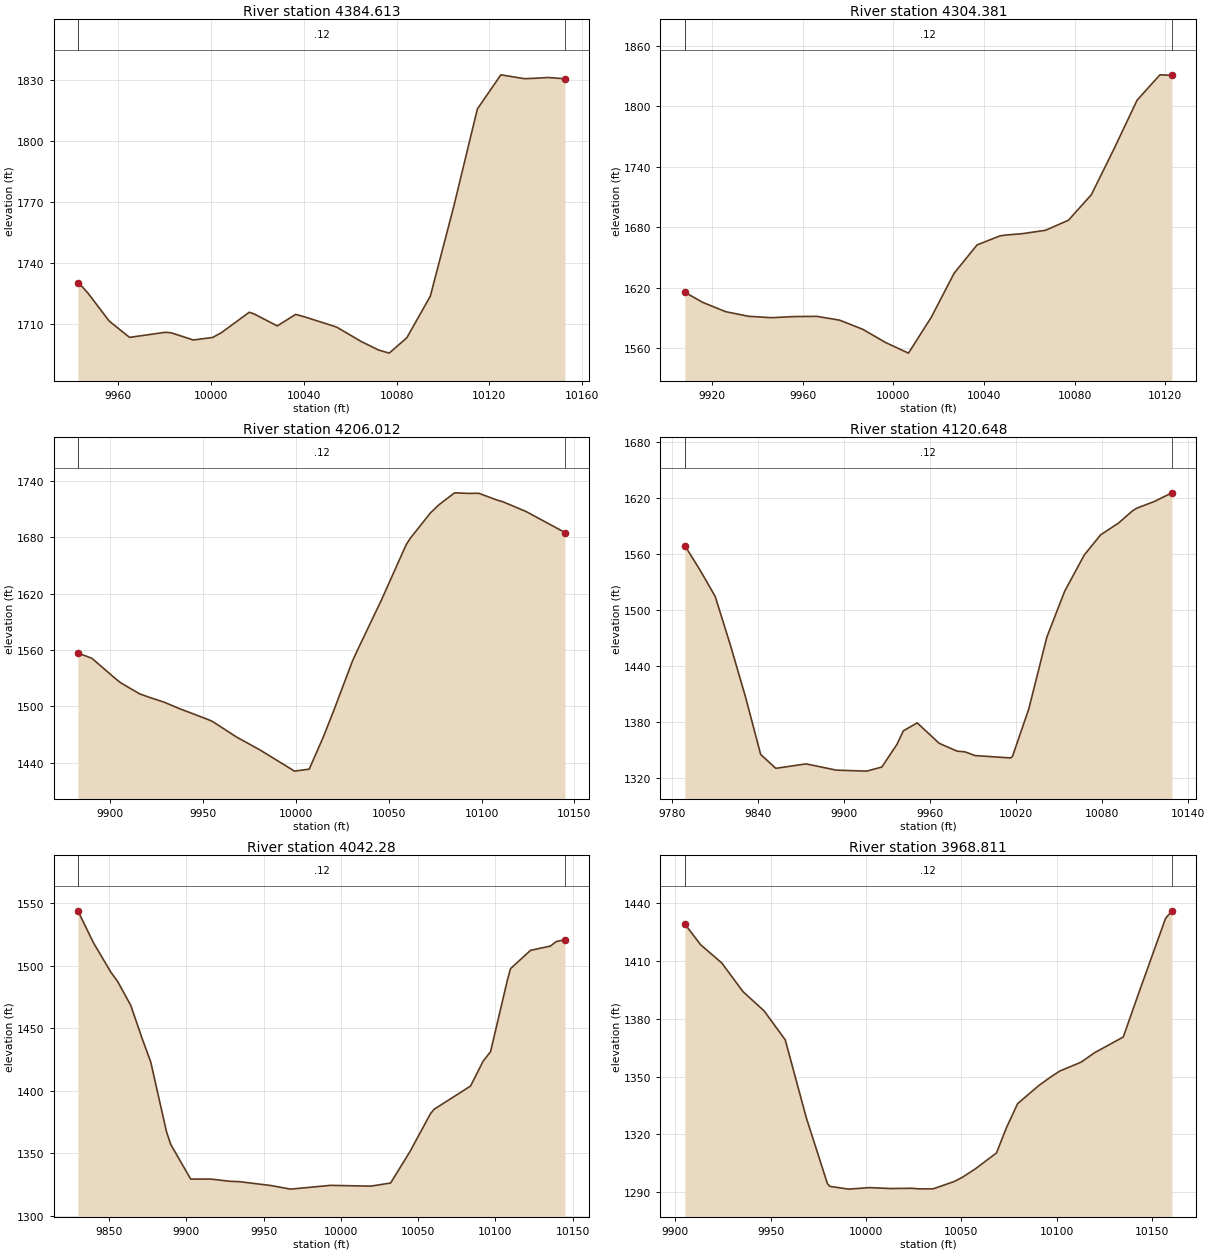
Type RM Length L Ch R = 1 ,4384.613,80.231300,80.231300,80.231300
XS GIS Cut Line= 3
705102.563754827776063.750953779705177.520765692          776175
705252.257810742776187.221233487
#Sta/Elev= 30
9942.706 1729.939944.2121728.5719947.0661724.941 9956.271711.1339964.9621703.196
9968.3281703.7459980.3861705.6979982.8581705.4649992.4441701.91910000.751703.155
 10004.51705.48610016.561715.56310018.651714.71310028.62 1708.8410036.551714.517
10040.681713.18310052.73 1708.8110054.441708.09710064.791701.15410072.341696.953
10076.85 1695.4510084.431703.00210094.56 1723.47 10104.71767.79510114.831815.548
10124.961832.34410135.09 1830.4610138.821830.59910145.231831.02310152.581830.402
#Mann= 3 , 0 , 0
9942.706    0.12       09942.706    0.12       010152.58    0.12       0
#XS Ineff= 2 , 0
       09970.184        10046.72       0
Bank Sta=9942.706,10152.58
Exp/Cntr=0.3,0.1

Type RM Length L Ch R = 1 ,4304.381,98.369800,98.369800,98.369800
XS GIS Cut Line= 2
705027.170398146776176.294660047705240.238579988776204.703750983
#Sta/Elev= 25
9907.9611615.706 9915.861605.6679925.9491596.4619936.0371591.8769946.1261590.454
9956.2141591.5799966.3031591.7819973.8291588.9479976.3911587.933 9986.481578.965
9996.5681565.84110006.661555.32310016.751590.99710026.831634.63710036.921662.621
10047.011671.59210049.491672.412 10057.11673.84410067.191677.19110077.281687.181
10087.36 1712.4310097.451758.26210107.541806.14610117.631831.32910122.921830.879
#Mann= 3 , 0 , 0
9907.961    0.12       09907.961    0.12       010122.92    0.12       0
#XS Ineff= 2 , 0
       0                               0
Bank Sta=9907.961,10122.92
Exp/Cntr=0.3,0.1

Type RM Length L Ch R = 1 ,4206.012,85.363700,85.363700,85.363700
XS GIS Cut Line= 2
705019.521796763776210.167037696705220.570747852776378.436268449
#Sta/Elev= 30
9882.7331556.7549890.2631551.1979902.9171529.6559905.8441525.0739915.9581513.422
9921.4241509.5469928.998 1504.719937.0051498.0149952.586  1486.39955.0781484.212
9968.1191467.5669981.1591453.3659999.328 1431.3210007.241433.42810014.911467.977
10020.281494.78610030.491548.11110033.321560.26410046.071612.948 10059.41671.727
10061.65  1678.710072.441705.51210077.23 1714.5510085.481726.96310092.811726.367
10098.521726.46610108.391719.27910111.561717.41710123.971707.10810144.911684.776
#Mann= 3 , 0 , 0
9882.733    0.12       09882.733    0.12       010144.91    0.12       0
#XS Ineff= 2 , 0
       0                               0
Bank Sta=9882.733,10144.91
Exp/Cntr=0.3,0.1

Type RM Length L Ch R = 1 ,4120.648,78.368200,78.368200,78.368200
XS GIS Cut Line= 3
704894.958859712776265.892562166705039.189628929776315.062142566
705151.733335257776464.756198525
#Sta/Elev= 30
9788.9811568.837 9799.591542.5229810.1551514.315 9820.72 1462.329831.2851406.588
 9841.851344.8769852.4151329.9179873.5461334.6989894.6761327.9719915.8061326.921
9926.3711331.3249936.9361355.6729941.3631370.1319951.0321378.6679966.3071356.787
9978.8181348.3699984.3131347.6179991.3291343.59810016.351341.02910017.591343.231
10028.861393.78110041.37 1470.3410053.881519.90910067.521558.69910078.911580.302
10091.421592.976 10100.81605.60710103.931608.77410116.441616.13110128.641625.375
#Mann= 3 , 0 , 0
9788.981    0.12       09788.981    0.12       010128.64    0.12       0
#XS Ineff= 2 , 0
       09940.292                       0
Bank Sta=9788.981,10128.64
Exp/Cntr=0.3,0.1

Type RM Length L Ch R = 1 , 4042.28,73.468700,73.468700,73.468700
XS GIS Cut Line= 2
704878.568999588776298.672282442705122.231586993776498.628576145
#Sta/Elev= 30
9829.8731543.7039839.8471518.4319851.1281494.8549855.6111487.2579864.0641468.233
9871.3751441.982    98771423.0099887.1381367.5969889.9361357.1259902.872 1329.42
9915.8081329.4169928.7451327.5999934.429 1327.349954.6171324.2839967.5531321.384
9993.4251324.405 10019.31323.76310032.231326.25610044.78 1351.4310058.111381.824
10060.541385.29110083.981403.73910092.071423.52110096.911431.18810107.831488.453
10109.851497.51710122.79 1512.1410135.72 1515.5710139.361519.12110145.081520.596
#Mann= 3 , 0 , 0
9829.873    0.12       09829.873    0.12       010145.08    0.12       0
#XS Ineff= 2 , 0
       0                               0
Bank Sta=9829.873,10145.08
Exp/Cntr=0.3,0.1

Type RM Length L Ch R = 1 ,3968.811,88.362200,88.362200,88.362200
XS GIS Cut Line= 2
704877.476342231776422.142562151705108.027041525776532.500953779
#Sta/Elev= 30
9904.9161429.1739913.2571418.3729924.3441408.938 9935.431394.0999946.5171384.108
9957.6031369.107 9968.691328.5889979.7771294.4169981.0171293.0839990.8631291.646
10001.951292.43510013.041291.94810024.121292.09210027.341291.80110035.211291.786
 10046.31295.603 10050.51297.74310057.381302.16510068.47 1310.4310073.661323.447
10079.561335.99910090.641345.35610096.821349.75410101.731352.92910112.821357.484
10119.981362.43810134.991370.55610143.151393.46710157.161432.04810160.521436.007
#Mann= 3 , 0 , 0
9904.916    0.12       09904.916    0.12       010160.52    0.12       0
#XS Ineff= 2 , 0
       0                               0
Bank Sta=9904.916,10160.52
Exp/Cntr=0.3,0.1

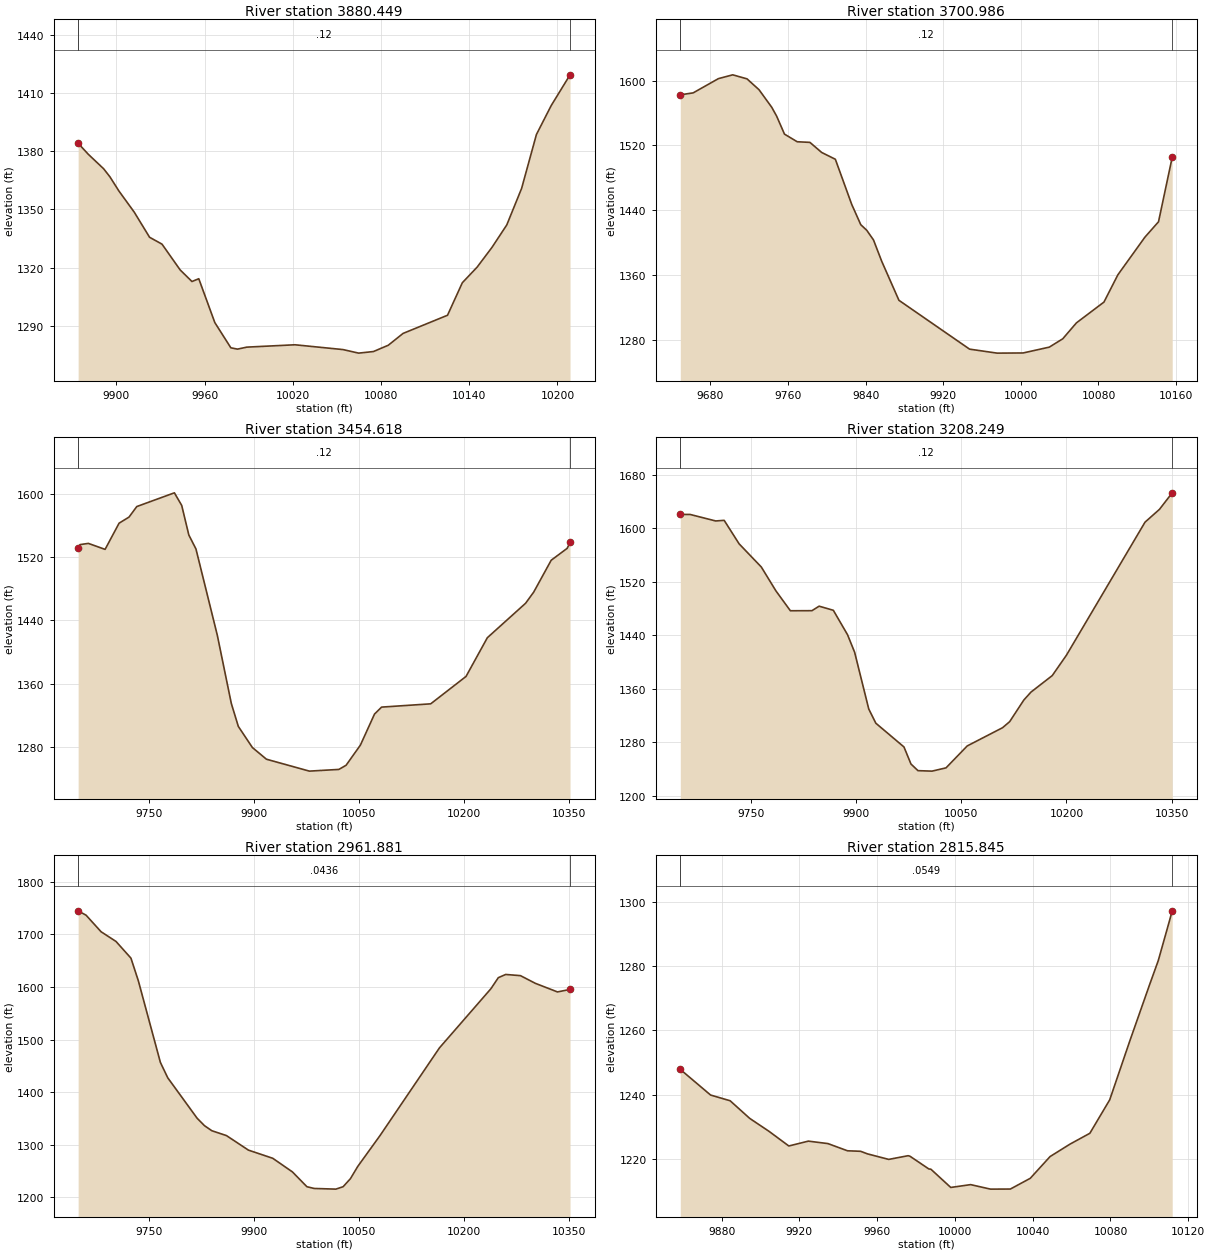
Type RM Length L Ch R = 1 ,3880.449,179.462300,179.462300,179.462300
XS GIS Cut Line= 4
704858.901167423776448.366338387704880.754314244776522.667037696
704981.278789788776566.373331398705127.694873691776547.798156574
#Sta/Elev= 30
9873.9431384.1169880.8571378.4279891.281 1370.979895.5571366.8169901.7051359.472
9912.1281348.5739922.5521335.6189930.9971332.0889943.3991318.7459951.3911312.806
 9956.021314.2489966.9241291.6449977.8291278.6279982.3211277.9389988.7331278.966
10021.451280.17910054.161277.70310064.761275.87410074.841276.69310084.92 1279.93
   10095 1286.0410125.241295.40910135.321312.175 10145.41320.24210155.481330.402
10165.561342.00110175.641360.81710185.721388.619 10195.81403.583 10208.61419.407
#Mann= 3 , 0 , 0
9873.943    0.12       09873.943    0.12       0 10208.6    0.12       0
#XS Ineff= 2 , 0
       0                               0
Bank Sta=9873.943,10208.6
Exp/Cntr=0.3,0.1

Type RM Length L Ch R = 1 ,3700.986,246.368500,246.368500,246.368500
XS GIS Cut Line= 6
 704785.25768581776891.659284176 704842.09211462776839.191319649
705007.753614379776696.454961983705035.925561336776668.438242285
705078.151238627776621.596604347705155.038466414776545.640333909
#Sta/Elev= 30
9649.0311582.393 9662.291584.7719688.3331602.3899703.0751607.0769717.8171602.076
9730.1921588.6329743.2971566.9249748.3361555.9939756.403 1533.829769.5091524.389
9782.6151523.6149794.7481511.1389808.827 1502.75 9825.691446.9989835.038 1421.89
9841.1611415.0439848.1441403.0449856.6321376.6389874.3561328.4839947.1351268.152
9975.4981263.21710002.351263.41510029.331270.63110043.191280.93310057.291300.624
10085.651326.29310099.981359.97110127.821406.43710141.88 1425.5410155.991505.185
#Mann= 3 , 0 , 0
9649.031    0.12       09649.031    0.12       010155.99    0.12       0
#XS Ineff= 2 , 0
       0                               0
Bank Sta=9649.031,10155.99
Exp/Cntr=0.3,0.1

Type RM Length L Ch R = 1 ,3454.618,246.368600,246.368600,246.368600
XS GIS Cut Line= 6
704782.778604002776935.957568593704871.556285502776885.962127012
704962.483572302776863.518259593 705044.39398255 776865.04343668
705234.207928341776900.036887696705458.905670864776857.063463032
#Sta/Elev= 30
9649.2071530.8759651.8571535.4859663.7881537.0149687.6491529.4529707.6431562.553
9721.7841570.2279732.8971583.5489786.514 1600.879796.9471585.0039807.106 1547.63
9817.2651530.0059847.7041421.1769867.7231334.8499877.7321305.8659897.7751279.222
9917.8281264.4639979.077 1249.4310021.16 1251.5910031.441256.84910051.851282.294
10071.991321.50610082.071330.27210152.16 1334.4210202.521369.01110232.931417.904
 10287.51461.42210299.111475.574   103241515.73410346.811530.783 10350.91538.235
#Mann= 3 , 0 , 0
9649.207    0.12       09649.207    0.12       0 10350.9    0.12       0
#XS Ineff= 2 , 0
       0                               0
Bank Sta=9649.207,10350.9
Exp/Cntr=0.3,0.1

Type RM Length L Ch R = 1 ,3208.249,246.368500,246.368500,246.368500
XS GIS Cut Line= 6
704737.892482761777200.891426826704832.366513091777161.525601367
 704923.22611031777138.299853314705016.618759948777124.484270348
705172.634498152 777114.44528704 705422.65032918777067.051931156
#Sta/Elev= 30
 9649.06 1620.41 9662.96 1620.429699.5271610.6799711.6751611.578 9732.991576.476
9764.6561541.8539785.4851506.199 9806.131476.4699836.8891476.5789847.122 1483.31
9867.4111477.165  9887.71440.6329897.8191414.4159917.9721329.6339928.0491308.427
9968.199 1272.919978.2161247.3829988.2181237.49510008.221236.79610028.221241.676
10058.441274.43410108.871301.673   101191310.71110139.251343.08510149.381354.868
10179.771379.58310200.02 1410.0510312.171608.90410332.771628.01110350.951652.713
#Mann= 3 , 0 , 0
 9649.06    0.12       0 9649.06    0.12       010350.95    0.12       0
#XS Ineff= 2 , 0
       0                               0
Bank Sta=9649.06,10350.95
Exp/Cntr=0.3,0.1

Type RM Length L Ch R = 1 ,2961.881,146.035500,146.035500,146.035500
XS GIS Cut Line= 6
704814.295746998777461.222217155704886.887165616777434.515889625
704951.406949072777413.681352834705112.093158442777364.660943262
705182.082587165777346.555533093705482.001057608777245.489991091
#Sta/Elev= 30
9649.0261744.7149660.4321736.3169681.7431704.9539703.0531686.4959724.3641654.777
  9734.91611.8579766.4251456.3419776.9341427.1369818.8411350.2669829.2961336.169
9839.7511326.5669860.6611317.2939892.0261289.6539926.7391274.1189954.7561248.283
9975.4841220.0479985.7981216.74410016.781215.47310027.141220.06610037.551235.303
 10048.11258.78210079.761317.248 10164.61484.07710238.051596.614 10248.61617.607
10259.15 1623.7110280.261621.42410301.361606.88910333.021590.47610350.961595.281
#Mann= 3 , 0 , 0
9649.026  0.0436       09649.026  0.0436       010350.96  0.0436       0
#XS Ineff= 2 , 0
       0                               0
Bank Sta=9649.026,10350.96
Exp/Cntr=0.3,0.1

Type RM Length L Ch R = 1 ,2815.845,109.325100,109.325100,109.325100
XS GIS Cut Line= 4
705069.510338098777485.257695854705161.705818892777475.379608601
705193.974237144777489.208930731705316.462518752777463.525903955
#Sta/Elev= 30
 9858.761247.9029874.3381239.9359884.3951238.1589894.4531232.682 9904.511228.605
9914.5671224.1019924.6241225.6099934.6821224.8479944.7391222.6089951.4831222.451
9955.0671221.6439965.947 1219.939975.9051221.0799976.8261220.936 9986.591216.957
9987.6381216.8819997.8561211.21110008.07 1212.0910018.291210.69110028.511210.716
10038.73 1214.0510048.941220.81810059.161224.67210069.381228.046 10079.61238.448
10089.811256.53910100.031274.10310104.561281.70910110.251293.90710111.741297.192
#Mann= 3 , 0 , 0
 9858.76  0.0549       0 9858.76  0.0549       010111.74  0.0549       0
#XS Ineff= 2 , 0
       0                               0
Bank Sta=9858.76,10111.74
Exp/Cntr=0.3,0.1

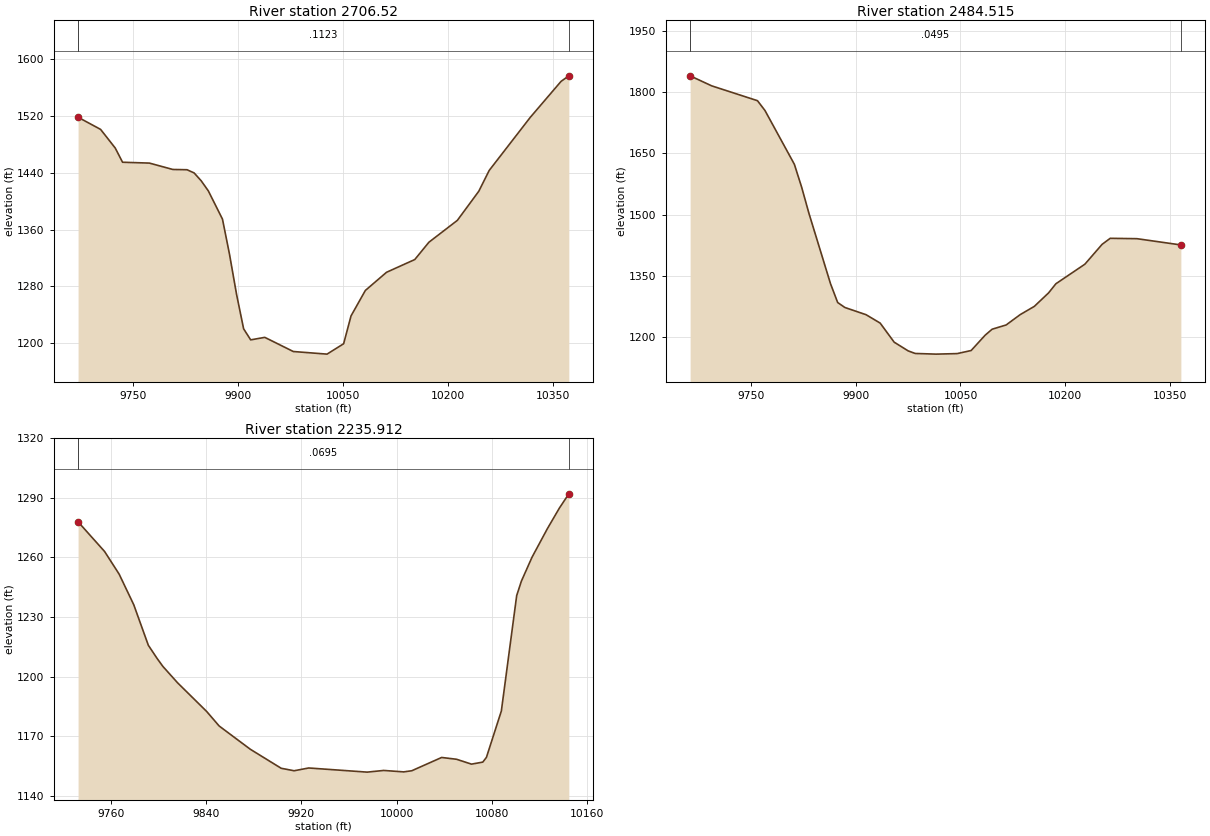
Type RM Length L Ch R = 1 , 2706.52,222.005500,222.005500,222.005500
XS GIS Cut Line= 6
704864.238021712777662.724448807704990.069405115777628.483113237
705163.521342497777601.470558808705229.883375957777560.762465085
705415.971344895777528.949072664705535.093209213777483.678251522
#Sta/Elev= 30
9671.1231518.3749703.3161501.2599724.2471474.9989734.712 1454.969773.1251453.752
9806.6081444.7669826.8971444.3849837.0411439.8779847.1861428.734 9857.331414.585
9877.547 1374.79 9887.631325.1199897.713 1268.589907.7961220.1259917.8791204.536
9938.0461208.071 9978.821188.11510027.051184.43410050.761199.06610061.361238.348
 10081.81274.16610112.121299.82910152.51 1317.79 10172.71342.18810213.371373.023
10244.041414.12610258.891443.41110317.611518.25410361.611568.96210372.721576.785
#Mann= 3 , 0 , 0
9671.123  0.1123       09671.123  0.1123       010372.72  0.1123       0
#XS Ineff= 2 , 0
       0                               0
Bank Sta=9671.123,10372.72
Exp/Cntr=0.3,0.1

Type RM Length L Ch R = 1 ,2484.515,248.602800,248.602800,248.602800
XS GIS Cut Line= 6
704857.117930567 777896.66416822704960.560580798777851.365981511
705064.907017312777823.179322786705363.215598947777800.994013192
 705434.12718827 777767.87921669705509.779812179777699.601471096
#Sta/Elev= 30
9663.3521839.7379694.1881815.2279759.6571778.9279770.3831754.9369812.432 1623.34
 9822.911566.9179833.3321502.9489864.1011331.3179874.3571285.1659884.6121273.053
9914.9341255.3869935.1121234.8629955.1741188.1279975.2181166.8259985.219 1160.54
10015.231158.92110045.231160.20910065.231167.73710085.231205.18410095.241219.881
10115.261230.25110135.391255.56710155.561275.69610176.091308.90210186.431331.081
10227.861378.89710252.58 1427.6110264.121442.22810302.241441.34710365.161426.022
#Mann= 3 , 0 , 0
9663.352  0.0495       09663.352  0.0495       010365.16  0.0495       0
#XS Ineff= 2 , 0
       0                               0
Bank Sta=9663.352,10365.16
Exp/Cntr=0.3,0.1

Type RM Length L Ch R = 1 ,2235.912,0.000000,0.000000,0.000000
XS GIS Cut Line= 6
 705136.75360829778233.183353898705271.297684958778042.403595539
705290.855623163778015.894005319705292.069703869778014.304663305
705344.410763769777944.973679136 705380.05584864777901.010626668
#Sta/Elev= 30
9732.6061277.9229754.8571262.9739767.0931251.554 9779.331236.1639791.5671215.753
9798.9681209.0789803.803 1205.08 9816.041196.8929840.5131182.4119851.0221175.086
9877.2231163.3469903.0761153.7929913.933 1152.55 9926.171153.9469975.2571151.859
9989.1371152.70610005.861151.98110012.661152.54710037.721159.24310050.251158.335
10062.781155.88410072.251156.90210075.311159.28310087.841182.64410100.711240.771
10104.681248.07610113.581260.08210126.461274.46110136.44 1284.7310144.471292.015
#Mann= 3 , 0 , 0
9732.606  0.0695       09732.606  0.0695       010144.47  0.0695       0
#XS Ineff= 2 , 0
       0                               0
Bank Sta=9732.606,10144.47
Exp/Cntr=0.3,0.1